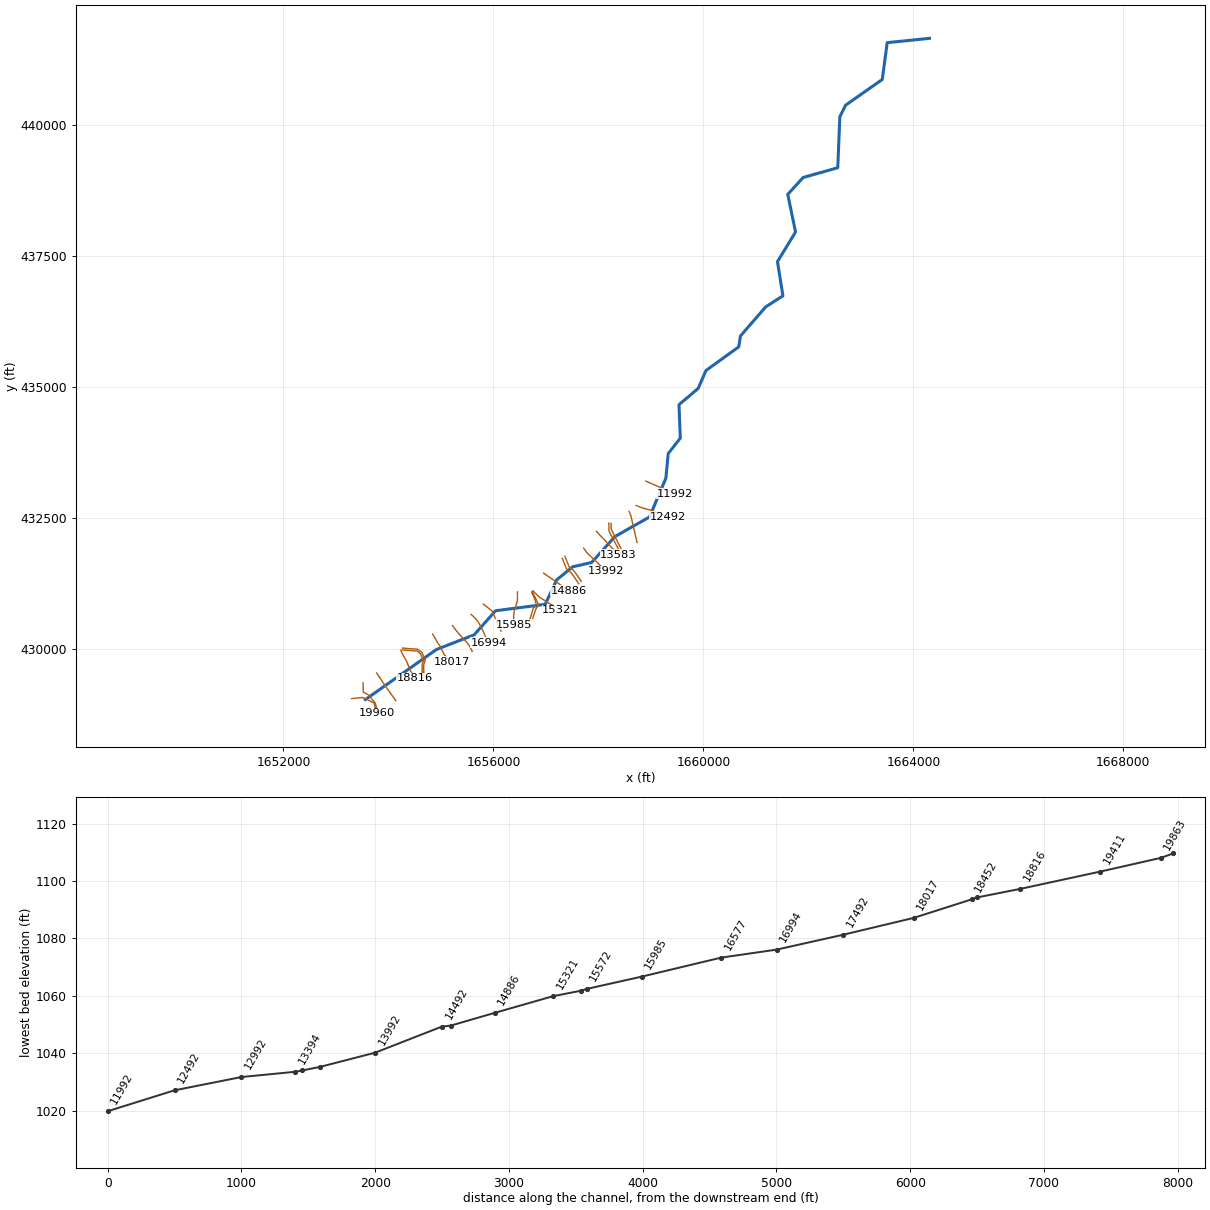
--- CARNEYFK.prj (project) ---

Proj Title=CARNEYFK
Current Plan=p01
Default Exp/Contr=0,0
English Units
Geom File=g01
Flow File=f01
Plan File=p01
BEGIN DESCRIPTION:
---------- MODELED AS PART OF WVEMD CTP PROGRAM, 2023----------
Stream Name: Carney Fork
Flood Zone:  AFH
Wetzel County, WV
HEC-RAS Version: RAS 6.3
Vertical Datum: NAVD88
Projection: NAD 1983 StatePlane West Virginia S FIPS 4702 (US Feet)
Terrain: 1-meter West Virginia FEMA R3 South Central (collected 2018-2020)
Land Use: 2019 NLCD
Hydrologic Method:
WV SIR2010-5033 regression equations
Additional Model Notes:
None
END DESCRIPTION:
DSS Export Rating Curves= 0
DSS Export Rating Curve Sorted= 0
DSS Export Volume Flow Curves= 0
DXF OffsetX= 0
DXF OffsetY= 0
DXF ScaleX= 0
DXF ScaleY= 0

--- CARNEYFK.p01 (plan) ---

Plan Title=Floodplain
Program Version=6.30
Short Identifier=Floodplain
Geom File=g01
Flow File=f01
Subcritical Flow
K Sum by GR= 0
Std Step Tol= 0.01
Critical Tol= 0.01
Num of Std Step Trials= 20
Max Error Tol= 0.3
Flow Tol Ratio= 0.001
Split Flow NTrial= 30
Split Flow Tol= 0.02
Split Flow Ratio= 0.02
Log Output Level= 0
Friction Slope Method= 1
Unsteady Friction Slope Method= 2
Unsteady Bridges Friction Slope Method= 1
Parabolic Critical Depth
Global Vel Dist= 0 , 0 , 0
Global Log Level= 0
CheckData=True
Encroach Param=-1 ,0,0, 0
Mapping Interval=1HOUR
Computation Time Step Use Courant=        0
Computation Time Step Use Time Series=    0
Computation Time Step Count To Double=0
Computation Time Step Max Doubling=0
Computation Time Step Max Halving=0
Computation Time Step Residence Courant=0
Run HTab= 0
Run UNet= 0
Run Sediment= 0
Run PostProcess= 0
Run WQNet= 0
Run RASMapper= 0
UNET Theta= 0
UNET Theta Warmup= 0
UNET ZTol= 0
UNET ZSATol= 0
UNET MxIter= 0
UNET Max Iter WO Improvement= 0
UNET MaxInSteps= 0
UNET DtIC= 0
UNET DtMin= 0
UNET MaxCRTS= 0
UNET WFStab= 0
UNET SFStab= 0
UNET WFX= 1
UNET SFX= 1
UNET Gravity=32.17405
UNET 1D Methodology=Finite Difference
UNET DSS MLevel= 1
UNET Pardiso=0
UNET DZMax Abort= 0
UNET Use Existing IB Tables= 0
UNET Froude Reduction=False
UNET Froude Limit= 0
UNET Froude Power= 0
UNET D1 Cores= 0
UNET WindReference=Eulerian
UNET WindDragFormulation=Hsu (1988)
UNET D2 Coriolis=0
UNET D2 Cores= 0
UNET D2 Theta= 1
UNET D2 Theta Warmup= 1
UNET D2 Z Tol= 0.01
UNET D2 Volume Tol= 0.01
UNET D2 Max Iterations= 20
UNET D2 Equation= 0
UNET D2 RampUpFraction=0.1
UNET D2 TimeSlices= 1
UNET D2 Turbulence Formulation=Non-Conservative (original)
UNET D2 Eddy Viscosity=0.3
UNET D2 Transverse Eddy Viscosity=0.1
UNET D2 Smagorinsky Mixing=0
UNET D2 BCVolumeCheck=0
UNET D2 Cores=0
UNET D2 SolverType=PARDISO (Direct)
UNET D2 Minimum Iterations= 3
UNET D2 Maximum Iterations= 30
UNET D2 Restart Number= 10
UNET D2 Relaxation Coeff=1.3
UNET D2 SOR Precondition Iterations= 10
UNET D2 ILUT Maximum Fill= 8
UNET D2 ILUT Tolerance=1E-08
UNET D2 Convergence Tolerance=0.00001
UNET D1D2 MaxIter= 0
UNET D1D2 ZTol=0.01
UNET D1D2 QTol=0.1
UNET D1D2 MinQTol=1
Write IC File= 0
Write IC File at Fixed DateTime=0
Write IC File at Sim End=0
Echo Input=False
Echo Parameters=False
Echo Output=False
Write Detailed= 0
HDF Write Warmup=0
HDF Write Time Slices=0
HDF Flush=0
HDF Compression= 1
HDF Chunk Size= 1
HDF Spatial Parts= 1
HDF Use Max Rows=0
HDF Fixed Rows= 1
Calibration Method= 0
Calibration Iterations= 20
Calibration Max Change=0.05
Calibration Tolerance=0.2
Calibration Maximum=1.5
Calibration Minimum=0.5
Calibration Optimization Method= 1
WQ AD Non Conservative
WQ ULTIMATE=-1
WQ Max Comp Step=1HOUR
WQ Output Interval=15MIN
WQ Output Selected Increments= 0
WQ Output face flow=0
WQ Output face velocity=0
WQ Output face area=0
WQ Output face dispersion=0
WQ Output cell volume=0
WQ Output cell surface area=0
WQ Output cell continuity=0
WQ Output cumulative cell continuity=0
WQ Output face conc=0
WQ Output face dconc_dx=0
WQ Output face courant=0
WQ Output face peclet=0
WQ Output face adv mass=0
WQ Output face disp mass=0
WQ Output cell mass=0
WQ Output cell source sink temp=0
WQ Output nsm pathways=0
WQ Output nsm derived pathways=0
WQ Create Restart=0
WQ Fixed Restart=0
WQ System Summary=0
WQ Write To DSS=0
Sorting and Armoring Iterations= 10
XS Update Threshold= 0.02
Bed Roughness Predictor= 0
Hydraulics Update Threshold= 0.02
Energy Slope Method= 1
Volume Change Method= 1
Sediment Retention Method= 0
Sediment TS Multiplier= 1
Warm Up Method= 0
XS Weighting Method= 0
Number of US Weighted Cross Sections= 1
Number of DS Weighted Cross Sections= 1
Upstream XS Weight=0
Main XS Weight=1
Downstream XS Weight=0
Number of DS XS's Weighted with US Boundary= 1
Upstream Boundary Weight= 1
Weight of XSs Associated with US Boundary= 0
Number of US XS's Weighted with DS Boundary= 1
Downstream Boundary Weight= 0.5
Weight of XSs Associated with DS Boundary= 0.5
Percentile Method= 0
Sediment Output Level= 3
Mass or Volume Output= 0
Output Increment Type= 1
Profile and TS Output Increment= 1
Transport Output Increment 1
XS Output Flag= 0
XS Output Increment= 10
Read HDF5 Sediment Hotstart= 0
Sediment Hotstart Type= 0
Write Gradation File= 0
Read Gradation Hotstart= 0
Write HDF5 File= 1
Write Binary Output= 1
Write DSS Sediment File= 0
DSS Sediment Output Type= 1
SV Curve= 0
Specific Gage Flag= 0
Subcell Erosion Methods= 0
Subcell Deposition Methods= 0
Advection Scheme= 1
Matrix Solver= 0
Implicit Weighting Factor= 1
Maximum Outer Loop Convergence Iterations= 5
Convergence Maximum Absolute= 0.001
Convergence RMSE= 0.0001
Grain Fractions Max Abs Error= 0.001
Max Subgrid Regions= 1
Max Subgrid Length Scale= 3.402823E+38
Initial Layer Thickness= 3.402823E+38
Min Layer Thickness= 3.402823E+38
Max Layer Thickness= 3.402823E+38
Number of Layers= 5

--- CARNEYFK.f01 (steady flow) ---

Flow Title=Flow
Program Version=4.00
Number of Profiles=1
Profile Names=F01pct
River Rch & RM=CARNEYFK,Main,19960
     668
River Rch & RM=CARNEYFK,Main,18490
     753
River Rch & RM=CARNEYFK,Main,17492
     838
River Rch & RM=CARNEYFK,Main,14555
     986
River Rch & RM=CARNEYFK,Main,13446
    1120
River Rch & RM=CARNEYFK,Main,9493
    1500
River Rch & RM=CARNEYFK,Main,3000
    1700
Boundary for River Rch & Prof#=CARNEYFK,Main      ,1
Up Type=0
Dn Type=3
Dn Slope=0.013989

--- CARNEYFK.g01 (geometry) ---

Geom Title=Geometry
Program Version=6.31

River Reach=CARNEYFK        ,Main
Reach XY= 30
     1653558.946      429044.449     1654913.408      429998.897
     1655633.702      430279.815     1656040.444      430737.694
     1656986.481      430860.154     1657204.487      431326.108
     1657508.955      431575.065     1657870.952      431657.154
     1658316.047      432152.376     1658973.429       432524.13
       1659285.5      433262.631      1659330.07      433733.093
     1659560.457      434026.782     1659535.265      434664.543
     1659900.869      434973.735     1660049.866      435315.869
     1660673.847      435765.015     1660706.144      435972.578
     1661187.802      436528.089     1661515.511      436737.589
      1661412.16      437389.131     1661756.122      437954.527
      1661607.47      438670.713     1661900.512      438992.332
     1662560.295      439179.338     1662600.153      440149.711
     1662709.198      440370.056     1663408.337      440860.131
     1663502.592      441562.279     1664308.157      441644.187

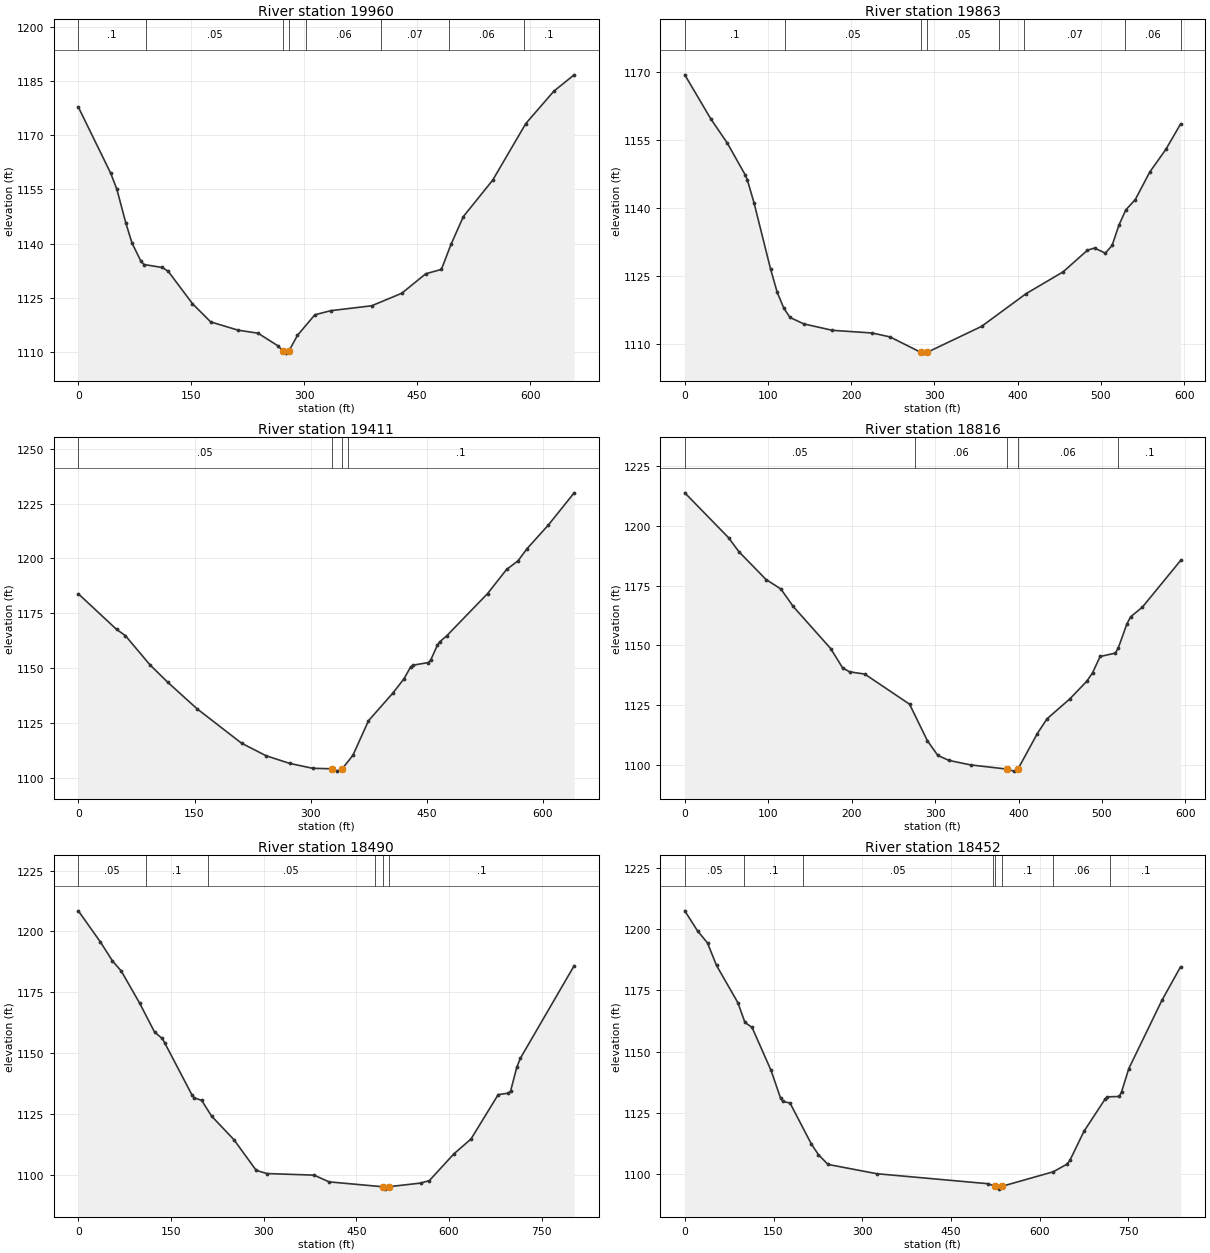
Type RM Length L Ch R = 1 ,19960   ,96.5,96.4,96.1
XS GIS Cut Line= 4
1653297.32146105429063.8311864671653508.44334849429085.957497814
1653724.17488412428981.7794485551653779.49066249428782.642646433
#Sta/Elev= 30
       0 1177.78      43 1159.46    51.1 1155.07    63.1 1145.67    71.2 1140.18
    83.2 1135.06    87.3 1134.18   111.4 1133.36   119.4  1132.3   151.6 1123.34
   175.8 1118.29   212.3    1116   238.6 1115.17   265.2 1111.66  271.25 1110.31
     276 1109.65   279.9 1110.32     291 1114.57   314.1 1120.26   335.1  1121.4
   389.6 1122.76   429.6 1126.23   461.4 1131.62   482.2 1132.83     495 1139.79
   511.3 1147.45   550.3 1157.54   594.3 1173.22   631.6 1182.19   658.5  1186.7
#Mann= 8 ,-1,0
       0      .1       0      90     .05       0  271.25    .045       0
   279.9     .05       0  302.28     .06       0  402.28     .07       0
  491.85     .06       0  591.85      .1       0
Bank Sta=271.25,279.9
XS Rating Curve= 0 ,0
Exp/Cntr(USF)=0,0
Exp/Cntr=0.3,0.1

Type RM Length L Ch R = 1 ,19863   ,449.7,452.7,451.2
XS GIS Cut Line= 6
1653515.45643763429363.5793538061653521.14186466429186.383544683
1653645.27368816429120.0535626581653679.38625034429059.409007664
 1653751.4016594428975.0751733761653773.19579635428880.318056198
#Sta/Elev= 30
       0 1169.31    31.1 1159.66    51.1 1154.29    72.8 1147.23    75.1 1146.23
    83.1 1141.21   103.1 1126.57   111.1 1121.43   119.1 1117.92   126.5 1115.91
   143.1  1114.5   177.3 1113.09   225.2  1112.5   246.6 1111.64  283.85 1108.22
   285.9 1108.07  290.96 1108.22   356.6 1113.95   410.1 1121.15   454.6 1125.95
   483.9 1130.72   492.4  1131.2   505.3 1130.07   513.5 1131.76   521.7 1136.23
   529.9 1139.57   541.4 1141.87   558.7  1147.9   578.1 1152.91   595.8  1158.5
#Mann= 8 ,-1,0
       0      .1       0     120     .05       0  283.85    .045       0
  290.96     .05       0  378.14      .1       0  407.72     .07       0
  528.61     .06       0  595.85      .1       0
Bank Sta=283.85,290.96
XS Rating Curve= 0 ,0
Exp/Cntr(USF)=0,0
Exp/Cntr=0.3,0.1

Type RM Length L Ch R = 1 ,19411   ,593.9,594.9,591.6
XS GIS Cut Line= 3
1653775.11718358429551.8249431181653923.38919958429328.774514422
1654139.39971151429025.417654854
#Sta/Elev= 30
       0 1183.95    49.3 1167.77    60.8  1164.9    92.5 1151.63   115.6 1143.66
   153.1 1131.71   210.8 1115.98   242.6 1110.26     273  1106.8   302.5 1104.58
   327.1 1104.36   334.5 1103.29   340.81104.363   354.6 1110.54   374.6 1126.19
   406.2 1138.83   420.4 1145.25   429.1 1150.71     432 1151.47   452.1 1152.69
     455 1153.83   463.6 1160.57   466.4 1162.04     476 1164.96   528.4 1184.05
   552.9    1195   567.7 1198.94   579.4 1204.48     607 1215.28   640.2 1229.87
#Mann= 4 ,-1,0
       0     .05       0   327.1    .045       0   340.8     .05       0
  347.84      .1       0
Bank Sta=327.1,340.8
XS Rating Curve= 0 ,0
Exp/Cntr(USF)=0,0
Exp/Cntr=0.3,0.1

Type RM Length L Ch R = 1 ,18816   ,325.2,325.9,324.2
BEGIN DESCRIPTION:
Structure XS 4
END DESCRIPTION:
XS GIS Cut Line= 6
1654234.47028435 429978.743852161654355.21249695429752.852899737
1654392.71865552429657.8711343181654425.54142452429584.000547147
1654470.09415695429502.7021533171654502.65208381429449.356407223
#Sta/Elev= 30
       0 1213.81    52.4 1195.04    64.9 1189.14    97.4 1177.52   115.2 1173.54
   129.9 1166.25   174.9 1148.59   189.1 1140.56   197.5 1138.87   215.7 1137.93
   269.4 1125.32   290.9 1109.95   303.3 1103.87   316.7 1101.78   342.5 1099.91
   386.1 1098.15   394.7  1097.3  399.371098.188   422.4 1112.94   434.1 1119.18
   461.3 1127.48   481.7 1134.89   488.7 1138.45   497.8 1145.29     516 1146.71
   519.4 1148.69   529.7 1158.75   534.3 1161.89   548.4 1165.93   594.3  1185.5
#Mann= 5 ,-1,0
       0     .05       0  276.14     .06       0   386.1    .045       0
  399.37     .06       0  519.09      .1       0
Bank Sta=386.1,399.37
XS Rating Curve= 0 ,0
Exp/Cntr(USF)=0,0
Exp/Cntr=0.3,0.1

Type RM Length L Ch R = 1 ,18490   ,37,37.5,38.2
BEGIN DESCRIPTION:
Structure XS 3
END DESCRIPTION:
XS GIS Cut Line= 6
  1654256.933606429991.6521257531654548.01837847429969.300836288
1654607.76970894 429918.33631531 1654666.7556892429788.665067662
1654640.51111815 429715.283156081654643.30741537429505.497807514
#Sta/Elev= 30
       0 1208.47    35.7 1195.71    55.3 1187.92    69.6 1183.73    99.5 1170.49
   123.5 1158.69   135.6 1156.15   139.6 1154.42   183.7 1133.08   187.7 1131.76
   199.8 1130.67   215.8 1124.23   251.9 1114.59     288 1101.98   305.4 1100.68
   381.6 1100.03     406 1097.27   492.8 1095.27     497 1094.29   502.91095.279
   554.7 1096.79   568.5 1097.82   607.8 1108.69   635.8 1114.87   679.8 1133.06
   695.8 1133.65   699.8 1134.43   709.8 1144.22   715.8 1148.02   802.8 1185.96
#Mann= 6 ,-1,0
       0     .05       0     110      .1       0     210     .05       0
  479.63      .1       0   492.8    .045       0   502.9      .1       0
Bank Sta=492.8,502.9
XS Rating Curve= 0 ,0
Exp/Cntr(USF)=0,0
Exp/Cntr=0.3,0.1

Type RM Length L Ch R = 1 ,18452   ,430.2,434.9,429.9
BEGIN DESCRIPTION:
Structure XS 2
END DESCRIPTION:
XS GIS Cut Line= 6
1654266.70606017430026.5591570351654555.68068431430004.871406402
 1654635.9807559429943.1021205581654702.35968994429805.365832424
1654671.68233258429705.8428470811654672.19054904429516.821878619
#Sta/Elev= 30
       0 1207.61    21.5 1199.41    38.4 1194.47    53.6 1185.25    89.7 1170.02
   101.7 1161.91   113.7 1159.87   145.8 1142.28   161.9 1130.93   165.9 1129.56
   177.9 1128.91     214 1112.12     226 1107.74   242.1 1103.77   324.5 1099.96
   512.5 1095.87524.74271094.832   530.9 1093.65536.54271094.825   622.9 1100.75
   646.3  1103.9     651 1105.39   674.9 1117.33   710.8  1130.6   714.6 1131.43
   734.6  1131.6   738.6 1133.61   750.7 1143.02   806.6 1170.94   838.3 1184.74
#Mann= 8 ,-1,0
       0     .05       0     100      .1       0     200     .05       0
  520.36      .1       0524.7427    .045       0536.5427      .1       0
  622.54     .06       0  719.26      .1       0
Bank Sta=524.7427,536.5427
XS Rating Curve= 0 ,0
Exp/Cntr(USF)=0,0
Exp/Cntr=0.3,0.1

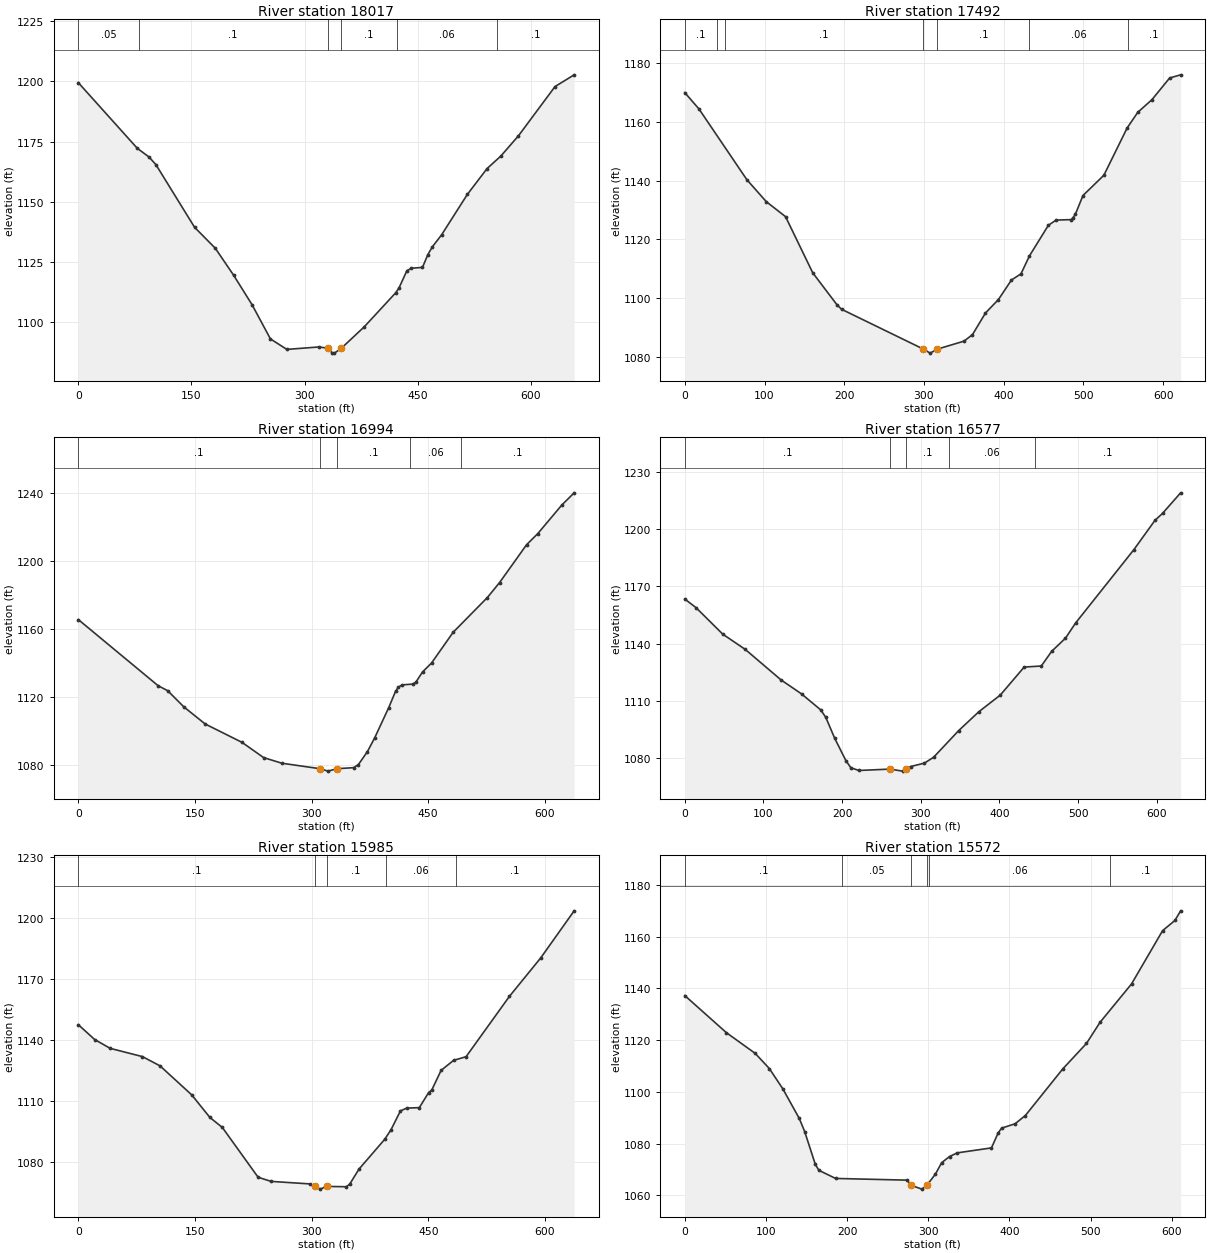
Type RM Length L Ch R = 1 ,18017   ,512,525.5,523.5
BEGIN DESCRIPTION:
Structure XS 1
END DESCRIPTION:
XS GIS Cut Line= 6
1654842.14490801430294.3824913351654939.00560668430126.073772833
1654988.99041484430054.7553459261655039.54264943429944.412344548
1655063.47265387429898.4836110251655215.51784892429764.026268587
#Sta/Elev= 30
       0 1199.47    78.2 1172.21    93.6 1168.64   102.8 1165.47   154.1 1139.43
   181.6 1130.72   205.9 1119.52   230.3 1107.29   254.7 1093.07   276.5 1088.72
   318.9 1089.73   330.6 1089.24   336.5  1087.3   339.6 1087.17   348.7  1089.2
   378.9 1098.03   420.6 1112.16   425.1 1114.19   435.6 1121.38   441.6 1122.43
   456.3 1122.76   463.4 1128.07   469.5 1131.36   481.6 1136.27   515.8 1153.08
   541.9  1163.8   560.1 1168.97   583.5 1177.39     632 1197.85   657.4 1202.73
#Mann= 6 ,-1,0
       0     .05       0      80      .1       0   330.6    .045       0
   348.7      .1       0  422.68     .06       0  554.47      .1       0
Bank Sta=330.6,348.7
XS Rating Curve= 0 ,0
Exp/Cntr(USF)=0,0
Exp/Cntr=0.3,0.1

Type RM Length L Ch R = 1 ,17492   ,488,497.9,491.9
XS GIS Cut Line= 6
1655218.79704183430456.3047396691655276.57087642430378.882978499
1655333.21315159430309.1524749251655502.45297059430124.348710671
1655552.06507608 430050.885931091655593.93277451429964.184004754
#Sta/Elev= 30
       0  1169.9    17.9  1164.3    77.9 1140.28   102.2 1132.83   126.4 1127.72
   160.5 1108.63   190.7 1097.83   196.6 1096.24   299.3 1082.69   307.8 1081.32
     3171082.696   350.3  1085.4   360.9 1087.61   377.2 1094.97   393.4 1099.53
   409.8 1106.19   421.7 1108.27   432.4  1114.4   456.1 1124.79   465.8 1126.56
   485.1 1126.72   487.1 1127.41   489.9  1128.5   499.5 1134.91   525.7  1141.8
   554.9 1157.88   568.3 1163.22     586  1167.5   608.2 1174.87     622 1175.95
#Mann= 7 ,-1,0
       0      .1       0      40     .05       0      50      .1       0
   299.3    .045       0     317      .1       0  432.03     .06       0
  555.67      .1       0
Bank Sta=299.3,317
XS Rating Curve= 0 ,0
Exp/Cntr(USF)=0,0
Exp/Cntr=0.3,0.1

Type RM Length L Ch R = 1 ,16994   ,403.6,416.6,411
XS GIS Cut Line= 6
  1655577.108005430668.0129776751655650.18266201430597.216531336
1655711.43549226430524.3154304181655795.30277859430365.680249006
1655861.43584843430214.7317320111655912.38784626430132.751252919
#Sta/Elev= 30
       0 1165.38   102.6 1126.45     115 1123.48   135.8 1113.95   163.2 1103.89
   210.6 1093.07   238.3 1084.12   261.7  1080.8     311 1077.55   321.2 1076.13
   332.9 1077.56   354.1 1078.17   360.2 1079.91     372 1087.67   381.1 1095.56
   399.4 1113.59   408.1  1123.1   411.6 1125.56   416.8 1126.93     430 1127.38
   434.1 1128.41   442.8 1134.52   454.4 1139.79   482.2 1157.89   526.2 1178.35
     542 1187.21   576.7 1209.47     591 1215.96   622.2 1232.94   637.9 1240.03
#Mann= 5 ,-1,0
       0      .1       0     311    .045       0   332.9      .1       0
  426.51     .06       0  492.56      .1       0
Bank Sta=311,332.9
XS Rating Curve= 0 ,0
Exp/Cntr(USF)=0,0
Exp/Cntr=0.3,0.1

Type RM Length L Ch R = 1 ,16577   ,587.1,592.8,581.6
XS GIS Cut Line= 3
 1655808.4036836430864.7570908551655976.61918578430729.617145603
1656144.67969838430350.664295933
#Sta/Elev= 30
       0 1163.39    14.2 1158.92    48.3    1145    76.8 1137.05   122.3 1121.08
   148.4 1113.74   172.8 1105.38   179.2 1101.48   190.6 1090.49   204.8  1078.8
   211.1 1075.09   221.3 1073.66   260.7 1074.38   276.8 1073.32   281.8 1074.33
     287 1075.72   304.5 1077.49   316.2 1080.54   348.2 1094.55   373.8 1104.41
   401.1 1113.14   431.4 1127.78   453.2 1128.35   466.4 1136.05   483.9  1142.9
     497 1150.97   570.9 1189.26   597.6 1204.53   607.3 1208.23   630.3 1218.99
#Mann= 5 ,-1,0
       0      .1       0   260.7    .045       0   281.8      .1       0
  335.78     .06       0  445.78      .1       0
Bank Sta=260.7,281.8
XS Rating Curve= 0 ,0
Exp/Cntr(USF)=0,0
Exp/Cntr=0.3,0.1

Type RM Length L Ch R = 1 ,15985   ,413.7,412.5,409.2
BEGIN DESCRIPTION:
Structure XS 4
END DESCRIPTION:
XS GIS Cut Line= 6
1656457.49928884431097.5167118461656458.91890542431001.277403012
1656452.66629326430911.7841436711656398.20511609430741.152595177
1656386.62803951430661.1583325861656385.73040351430469.563899502
#Sta/Elev= 30
       0 1147.49      21 1140.21      41 1135.87    82.4 1131.82     105 1127.29
   145.8 1113.02   169.2 1101.92   185.2    1097   231.2 1072.54   247.9 1070.51
   297.5 1069.28   303.9 1068.08     311 1066.71   319.4 1068.04   344.7 1067.89
   348.9 1069.11   360.9 1076.54     394  1091.2   402.1  1095.9   414.2 1105.14
   422.3 1106.52   438.5 1106.75   450.5 1114.17   454.5 1115.41   466.5 1125.05
   482.5 1129.97   498.6 1131.77   554.4 1161.44   594.6 1180.31   637.6 1203.44
#Mann= 5 ,-1,0
       0      .1       0   303.9    .045       0   319.4      .1       0
  395.08     .06       0  485.91      .1       0
Bank Sta=303.9,319.4
XS Rating Curve= 0 ,0
Exp/Cntr(USF)=0,0
Exp/Cntr=0.3,0.1

Type RM Length L Ch R = 1 ,15572   ,40,41.1,42.2
BEGIN DESCRIPTION:
Structure XS 3
END DESCRIPTION:
XS GIS Cut Line= 6
1656728.57665154431092.2874161381656793.29611223430941.275341195
1656815.69900247430860.7908836711656791.63663888430809.347209789
1656762.59585523430796.0714229811656682.94113438 430533.87463352
#Sta/Elev= 30
       0 1137.21    51.2 1122.89    86.8 1114.86   104.2    1109   120.7 1101.22
     141 1089.77   147.7 1084.68   160.7  1072.1   165.1  1069.7   185.8 1066.54
     274 1065.88   278.7  1063.9   292.2 1062.41   298.2 1063.86   308.8 1068.19
   316.5 1072.62   326.2    1075   335.8 1076.43   377.9 1078.34   386.2 1084.17
   390.4 1085.97     407 1087.67   419.7 1090.86   465.6 1108.81     495 1118.72
   511.7 1126.88   550.5  1141.7   588.8  1162.3     604 1166.25     611 1169.96
#Mann= 6 ,-1,0
       0      .1       0   194.3     .05       0   278.7    .045       0
   298.2     .05       0  301.52     .06       0   524.4      .1       0
Bank Sta=278.7,298.2
XS Rating Curve= 0 ,0
Exp/Cntr(USF)=0,0
Exp/Cntr=0.3,0.1

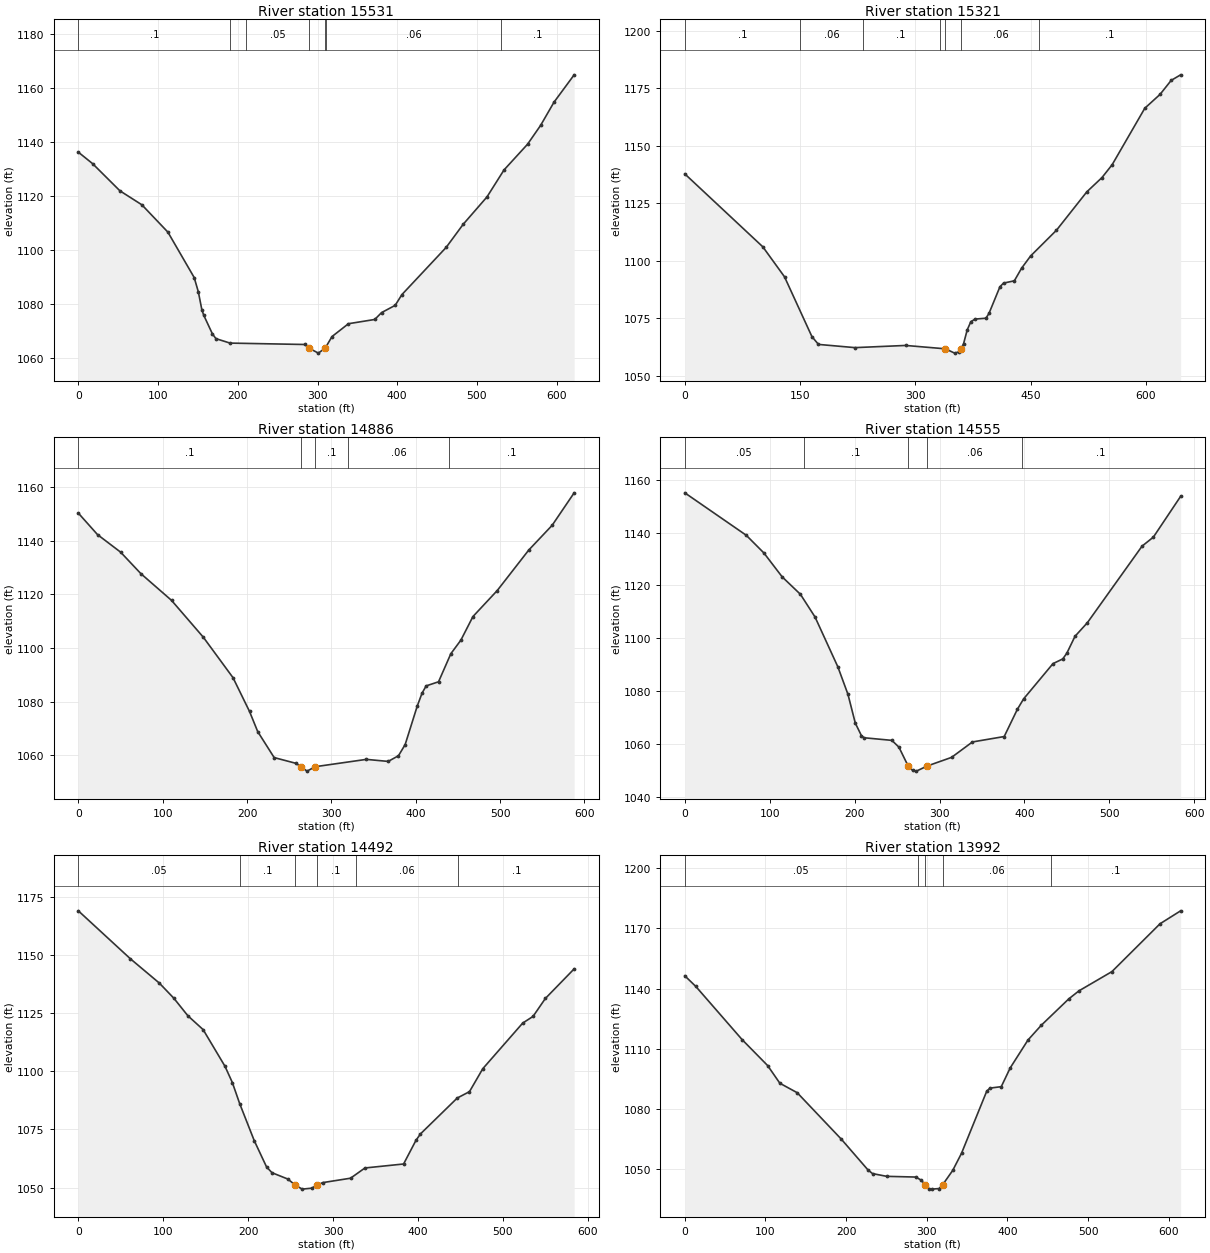
Type RM Length L Ch R = 1 ,15531   ,194.3,210.3,221.3
BEGIN DESCRIPTION:
Structure XS 2
END DESCRIPTION:
XS GIS Cut Line= 6
1656742.68217502431100.5847828931656848.05873281430878.215353857
1656847.22899613430843.366413485 1656831.4639993 430801.87957971
1656813.20979244430784.4551095241656725.25770483430528.066476792
#Sta/Elev= 30
       0 1136.33    17.8  1132.1    52.2 1121.99    79.7 1116.81   112.3 1106.69
   145.3 1089.85   150.5 1084.56   154.9 1077.95   157.3 1075.86   168.2 1068.93
   172.6 1067.18   190.3 1065.53     284 1065.01   289.7 1063.61     301 1061.81
   309.6 1063.64   318.2 1067.96   338.8 1072.72   371.8 1074.29   380.3 1076.83
   397.4 1079.53   405.9 1083.53   461.4 1101.03   482.7 1109.58   512.6 1119.75
   533.9 1129.73   563.4 1139.26   579.8 1146.25   596.6 1154.86   621.9 1165.01
#Mann= 7 ,-1,0
       0      .1       0  190.73     .06       0  210.73     .05       0
   289.7    .045       0   309.6     .05       0  310.93     .06       0
  530.55      .1       0
Bank Sta=289.7,309.6
XS Rating Curve= 0 ,0
Exp/Cntr(USF)=0,0
Exp/Cntr=0.3,0.1

Type RM Length L Ch R = 1 ,15321   ,433.3,434.7,433.3
BEGIN DESCRIPTION:
Structure XS 1
END DESCRIPTION:
XS GIS Cut Line= 3
1656751.93334163431118.2474465521656873.78056975 430997.69743513
1657275.67042021430747.066211496
#Sta/Elev= 30
       0 1137.83   101.5 1106.11   129.7 1093.08   165.4 1067.04   173.9 1063.67
   221.3 1062.27   287.3 1063.22   339.1 1061.75     351 1059.88   356.9 1060.47
   359.8 1061.87   362.7 1064.05   367.4    1070   372.1 1073.56   377.7 1074.69
   391.7 1075.06   395.7 1077.14   409.9 1088.71   414.6 1090.33   428.7 1091.33
   438.1 1096.81   449.8 1102.11   483.5 1113.33     523 1130.03   542.7 1136.23
     556 1141.86   598.4 1166.38   618.2 1172.39   632.7 1178.49     645 1180.91
#Mann= 7 ,-1,0
       0      .1       0     150     .06       0   231.4      .1       0
   331.4     .06       0   339.1    .045       0   359.8     .06       0
   461.4      .1       0
Bank Sta=339.1,359.8
XS Rating Curve= 0 ,0
Exp/Cntr(USF)=0,0
Exp/Cntr=0.3,0.1

Type RM Length L Ch R = 1 ,14886   ,330.1,330.8,330
BEGIN DESCRIPTION:
Structure XS 4
END DESCRIPTION:
XS GIS Cut Line= 2
1656957.41203302431453.1292784391657440.18940582431117.650821729
#Sta/Elev= 30
       0 1150.26    22.8 1142.23    50.1 1135.72    74.2 1127.68   110.5 1117.74
   148.2    1104   183.4 1088.92     203 1076.32   212.7 1068.82   232.2 1059.14
   258.1 1056.99   263.9 1055.73   263.9 1055.72   271.2 1054.09   280.9 1055.74
   341.5 1058.47   367.4 1057.71   379.6 1059.83   387.5 1063.98   401.8 1078.29
   407.5 1083.12   412.4 1085.86   427.1 1087.39   441.7 1097.86   453.6 1102.92
   467.9 1111.71   496.7  1121.4     534 1136.47   561.8 1145.71   587.9 1157.82
#Mann= 5 ,-1,0
       0      .1       0   263.9    .045       0   280.9      .1       0
     320     .06       0     440      .1       0
Bank Sta=263.9,280.9
XS Rating Curve= 0 ,0
Exp/Cntr(USF)=0,0
Exp/Cntr=0.3,0.1

Type RM Length L Ch R = 1 ,14555   ,63.4,63.4,63.6
BEGIN DESCRIPTION:
Structure XS 3
END DESCRIPTION:
XS GIS Cut Line= 5
1657312.66007248431735.1442223221657392.64579288 431533.78373897
 1657470.0409793431470.4590624561657521.54907838431408.000745734
1657625.44599148431253.211496405
#Sta/Elev= 30
       0 1155.11    72.4 1139.02    93.2  1132.3   114.7 1123.25   136.2 1116.64
   153.4 1108.04   180.3 1089.13   192.2 1078.71   200.8 1067.83     208  1063.1
   211.1 1062.27   243.9 1061.28   252.2 1058.71   262.9 1051.66   268.3 1049.92
   272.8 1049.62   285.4 1051.55   314.2 1054.83   338.8 1060.68   376.2 1062.73
   391.7 1073.05   399.1 1077.02   433.7 1090.38   445.2 1092.15     450 1094.34
   459.6 1100.73   474.1 1105.85   538.6 1134.91   551.9 1138.32     584 1153.77
#Mann= 5 ,-1,0
       0     .05       0     140      .1       0   262.9    .045       0
   285.4     .06       0  396.67      .1       0
Bank Sta=262.9,285.4
XS Rating Curve= 0 ,0
Exp/Cntr(USF)=0,0
Exp/Cntr=0.3,0.1

Type RM Length L Ch R = 1 ,14492   ,500,500,496.2
BEGIN DESCRIPTION:
Structure XS 2
END DESCRIPTION:
XS GIS Cut Line= 5
1657361.13167994431777.1072098651657441.11740033431575.746726513
1657518.51258676431512.4220499991657570.02068584431449.963733278
1657673.91759893431295.174483949
#Sta/Elev= 30
       0 1168.89    61.3 1148.29    95.3 1137.88   112.5 1131.34     129 1123.81
     147 1117.85   172.8 1102.06   181.4 1095.12     190  1086.1   207.2 1070.14
   221.7 1058.85   228.1 1056.37   246.7 1053.66  255.67 1051.01   263.7 1049.32
   275.1 1049.74   280.8 1050.97   287.7 1052.11   320.6 1054.01   337.6 1058.41
   383.1 1060.12   397.6 1070.23     403 1073.05   446.3 1088.46   460.7  1091.2
   476.4 1101.07   523.4 1120.66   535.6 1123.54   550.1 1131.24     584 1143.95
#Mann= 6 ,-1,0
       0     .05       0     190      .1       0  255.67    .045       0
   280.8      .1       0  326.67     .06       0  447.62      .1       0
Bank Sta=255.67,280.8
XS Rating Curve= 0 ,0
Exp/Cntr(USF)=0,0
Exp/Cntr=0.3,0.1

Type RM Length L Ch R = 1 ,13992   ,409.3,409.1,407.3
BEGIN DESCRIPTION:
Structure XS 1
END DESCRIPTION:
XS GIS Cut Line= 6
1657719.56533426431930.9425384251657774.13641934431851.902998343
1657836.48504792431790.4880949261657890.93113326431738.906833261
1657963.52711667431670.1333487631658149.55200709431493.898136929
#Sta/Elev= 30
       0 1146.36    13.6 1141.09    71.1 1114.59   102.7  1101.7   117.9 1092.89
   139.4 1088.18   194.1 1065.06   227.1 1049.78   232.8 1047.94   250.4 1046.57
   286.5 1046.22   293.3 1044.62   297.9 1042.46   302.7 1040.47   306.3 1040.21
   315.3 1040.49  319.811042.439   332.2 1049.52   343.1 1058.02   374.3 1088.86
   378.3 1090.47   392.4 1091.19   403.5 1100.53   425.5 1114.39     442 1121.74
   476.1 1134.87   488.8 1138.89   529.6 1148.44   589.3 1172.26   614.8 1178.69
#Mann= 5 ,-1,0
       0     .05       0  288.56      .1       0   297.9    .045       0
  319.81     .06       0  453.56      .1       0
Bank Sta=297.9,319.81
XS Rating Curve= 0 ,0
Exp/Cntr(USF)=0,0
Exp/Cntr=0.3,0.1

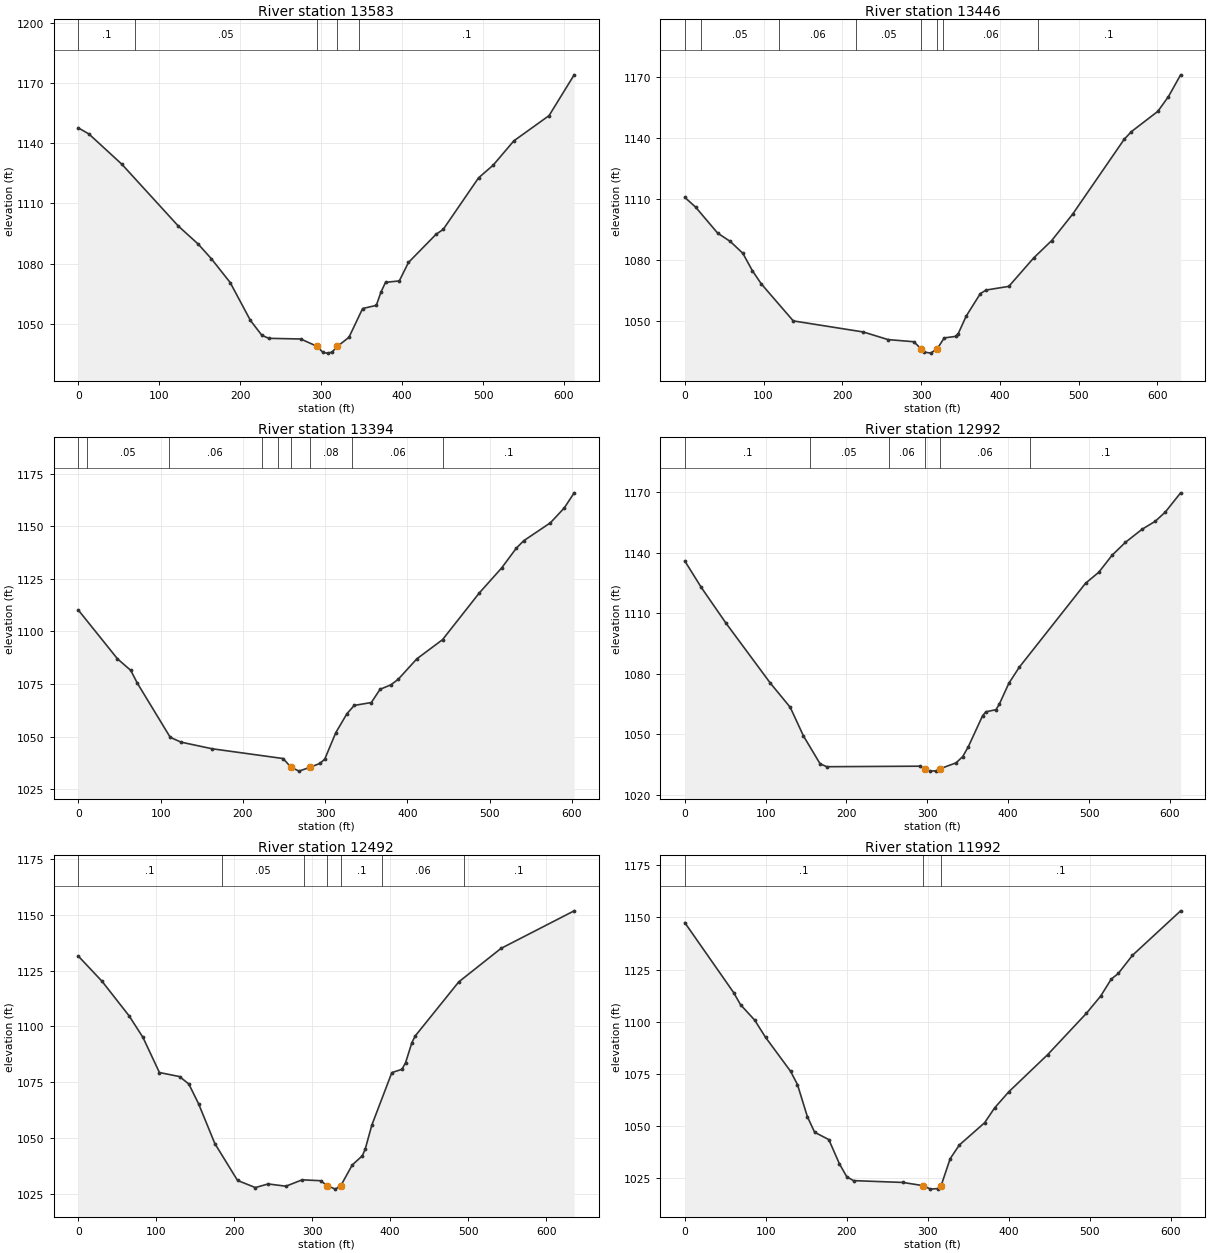
Type RM Length L Ch R = 1 ,13583   ,138.5,136.6,132.6
BEGIN DESCRIPTION:
Structure XS 4
END DESCRIPTION:
XS GIS Cut Line= 6
1657963.17566011432248.1239217511658087.72856062432116.449644415
1658207.98685029431989.316040425 1658259.5257892431934.829928918
1658319.09194303431870.730647667 1658382.6062517431801.719302757
#Sta/Elev= 30
       0 1147.68      13 1144.68    53.8 1129.54   123.6 1098.67   148.1  1089.7
   164.5 1082.31   187.6 1070.51   212.6  1051.6   226.7 1044.21   235.2 1042.68
   274.8 1042.34   294.6 1038.73   302.3 1035.61   307.8 1035.29   313.3 1035.75
   320.1 1038.68   334.3 1043.19   351.2 1057.54   368.1 1059.12   373.9 1065.82
   379.5 1070.62   396.5 1071.33   407.8 1080.53   441.8 1094.55   450.8 1097.07
   494.4 1122.76   512.5 1129.11     538 1141.22   581.5 1153.82   612.5 1174.17
#Mann= 5 ,-1,0
       0      .1       0      70     .05       0   294.6    .045       0
   320.1     .05       0  346.25      .1       0
Bank Sta=294.6,320.1
XS Rating Curve= 0 ,0
Exp/Cntr(USF)=0,0
Exp/Cntr=0.3,0.1

Type RM Length L Ch R = 1 ,13446   ,54,52.5,52.8
BEGIN DESCRIPTION:
Structure XS 3
END DESCRIPTION:
XS GIS Cut Line= 3
1658199.31626518432406.187535897 1658201.3325253432258.328460321
1658423.12113867431830.881314566
#Sta/Elev= 30
       0 1110.62    13.7 1105.83    41.7 1093.03    57.7 1088.94    73.7  1083.1
    85.7 1074.61    97.1 1068.06   137.7 1049.85   226.5 1044.41     258 1040.66
   290.7  1039.6     3001036.106   303.1 1034.58   312.1    1034   320.4 1036.11
   329.3 1041.48   343.7 1042.23   347.1 1043.59   357.2 1052.21   375.2  1063.3
   382.7 1065.04   411.3 1066.83   442.8 1080.79   465.8 1089.39   492.5 1102.45
   557.7 1139.14     567 1142.97   600.5 1152.93   613.9 1160.16   629.4 1170.88
#Mann= 8 ,-1,0
       0      .1       0      20     .05       0     120     .06       0
  217.87     .05       0     300    .045       0   320.4     .05       0
  327.87     .06       0  447.87      .1       0
Bank Sta=300,320.4
XS Rating Curve= 0 ,0
Exp/Cntr(USF)=0,0
Exp/Cntr=0.3,0.1

Type RM Length L Ch R = 1 ,13394   ,403.9,401.7,399.8
BEGIN DESCRIPTION:
Structure XS 2
END DESCRIPTION:
XS GIS Cut Line= 3
1658241.65772773432404.1712757751658244.34607456432291.260708972
 1658464.1184278 431853.73226261
#Sta/Elev= 30
       0 1110.21    47.6 1086.99    63.7  1081.5    71.7 1075.42   111.7 1049.64
   124.9 1047.34   162.5  1044.2   248.9 1039.54  258.211035.495   268.2 1033.55
   281.7 1035.41   281.7 1035.43   293.6  1037.2   299.5 1039.28   312.9 1051.85
   326.4 1060.85   335.3 1064.82   356.1  1066.2   366.7 1072.49   379.8  1074.6
   388.7 1077.23   411.4 1086.99   442.6  1096.1   487.2 1118.29   514.4  1130.2
   532.3 1139.66   541.2 1143.16   573.7 1151.72   590.5 1158.75   602.6 1165.99
#Mann= 9 ,-1,0
       0      .1       0      10     .05       0     110     .06       0
  222.94     .05       0  242.94     .08       0  258.21    .045       0
   281.7     .08       0  332.94     .06       0  442.94      .1       0
Bank Sta=258.21,281.7
XS Rating Curve= 0 ,0
Exp/Cntr(USF)=0,0
Exp/Cntr=0.3,0.1

Type RM Length L Ch R = 1 ,12992   ,488.5,499.9,506.6
BEGIN DESCRIPTION:
Structure XS 1
END DESCRIPTION:
XS GIS Cut Line= 6
1658585.61707984432631.5625282531658619.95264108 432543.48101151
1658639.55693258  432458.20559151658656.36004859432385.111905679
1658715.17095459432129.2846614271658737.62399368432038.251050845
#Sta/Elev= 30
       0 1135.91    20.4 1122.78    50.5 1105.33   105.8 1075.35   130.4 1063.37
   146.8 1049.15   167.3 1035.39   175.5 1033.91   290.5 1034.17  296.941032.813
   302.8 1031.72     311 1031.88   315.1  1032.8   335.6 1035.84   343.8 1038.95
   350.8 1043.92   368.4 1059.23   372.5 1061.13   384.9 1062.19     389  1064.9
   400.8 1075.25   413.6 1083.16   495.7 1124.86   512.1 1130.32   528.5 1138.73
     545 1145.13   565.6 1151.61   582.1 1155.63   594.5 1160.21   613.3 1169.68
#Mann= 6 ,-1,0
       0      .1       0  154.54     .05       0  252.04     .06       0
  296.94    .045       0   315.1     .06       0  427.04      .1       0
Bank Sta=296.94,315.1
XS Rating Curve= 0 ,0
Exp/Cntr(USF)=0,0
Exp/Cntr=0.3,0.1

Type RM Length L Ch R = 1 ,12492   ,499.1,500.1,498.1
XS GIS Cut Line= 6
1658719.99246725432744.5104650861658816.08709134432704.321569085
1658908.05508326 432677.343276591658985.05525734432657.381702334
1659149.07986367432596.3486879171659317.28950101432528.545673922
#Sta/Elev= 30
       0 1131.46    30.5 1120.14    65.2 1104.66    82.9 1095.04     104 1079.32
   129.8  1077.5   141.7 1074.19   154.2 1065.33   175.1 1047.49   204.2 1030.98
     227 1027.79   243.4 1029.41   266.2  1028.4   287.1 1031.26   310.7 1030.86
  318.991028.675   329.6 1027.09   336.6 1028.63   351.3 1037.92   364.2 1042.01
   367.9 1044.98   376.4 1055.76   402.1 1079.29     415 1080.76   419.6 1083.62
   427.8 1092.72     432 1095.67   487.9 1119.91   542.1 1134.91   635.9 1151.74
#Mann= 7 ,-1,0
       0      .1       0  184.16     .05       0  289.55      .1       0
  318.99    .045       0   336.6      .1       0  389.55     .06       0
  494.57      .1       0
Bank Sta=318.99,336.6
XS Rating Curve= 0 ,0
Exp/Cntr(USF)=0,0
Exp/Cntr=0.3,0.1

Type RM Length L Ch R = 1 ,11992   ,491.1,500,504.4
XS GIS Cut Line= 6
1658900.88941517433208.4015976791659067.22668092433136.405678675
1659227.82839385433066.8920381671659296.63665517433037.051546678
1659376.75657368433001.8774044221659462.53264885432964.036600843
#Sta/Elev= 30
       0 1147.48    60.3 1113.99    68.9 1108.14    86.3 1100.79    99.7 1092.57
   130.6  1076.3   139.2 1069.89   151.4 1054.54   160.4 1047.05   177.9 1043.54
     191 1031.94   200.1 1025.72   208.4 1023.88   269.4    1023   294.4 1021.47
   303.5  1019.8     313 1020.09  316.681021.529   327.8 1034.37   339.1 1040.93
   370.4 1051.62   382.7 1058.71   400.2 1066.42   448.2 1084.22   496.2 1104.08
   513.7 1112.28   526.8 1120.42   535.5 1123.14     553 1131.82   612.5 1153.14
#Mann= 3 ,-1,0
       0      .1       0   294.4    .045       0  316.68      .1       0
Bank Sta=294.4,316.68
XS Rating Curve= 0 ,0
Exp/Cntr(USF)=0,0
Exp/Cntr=0.3,0.1