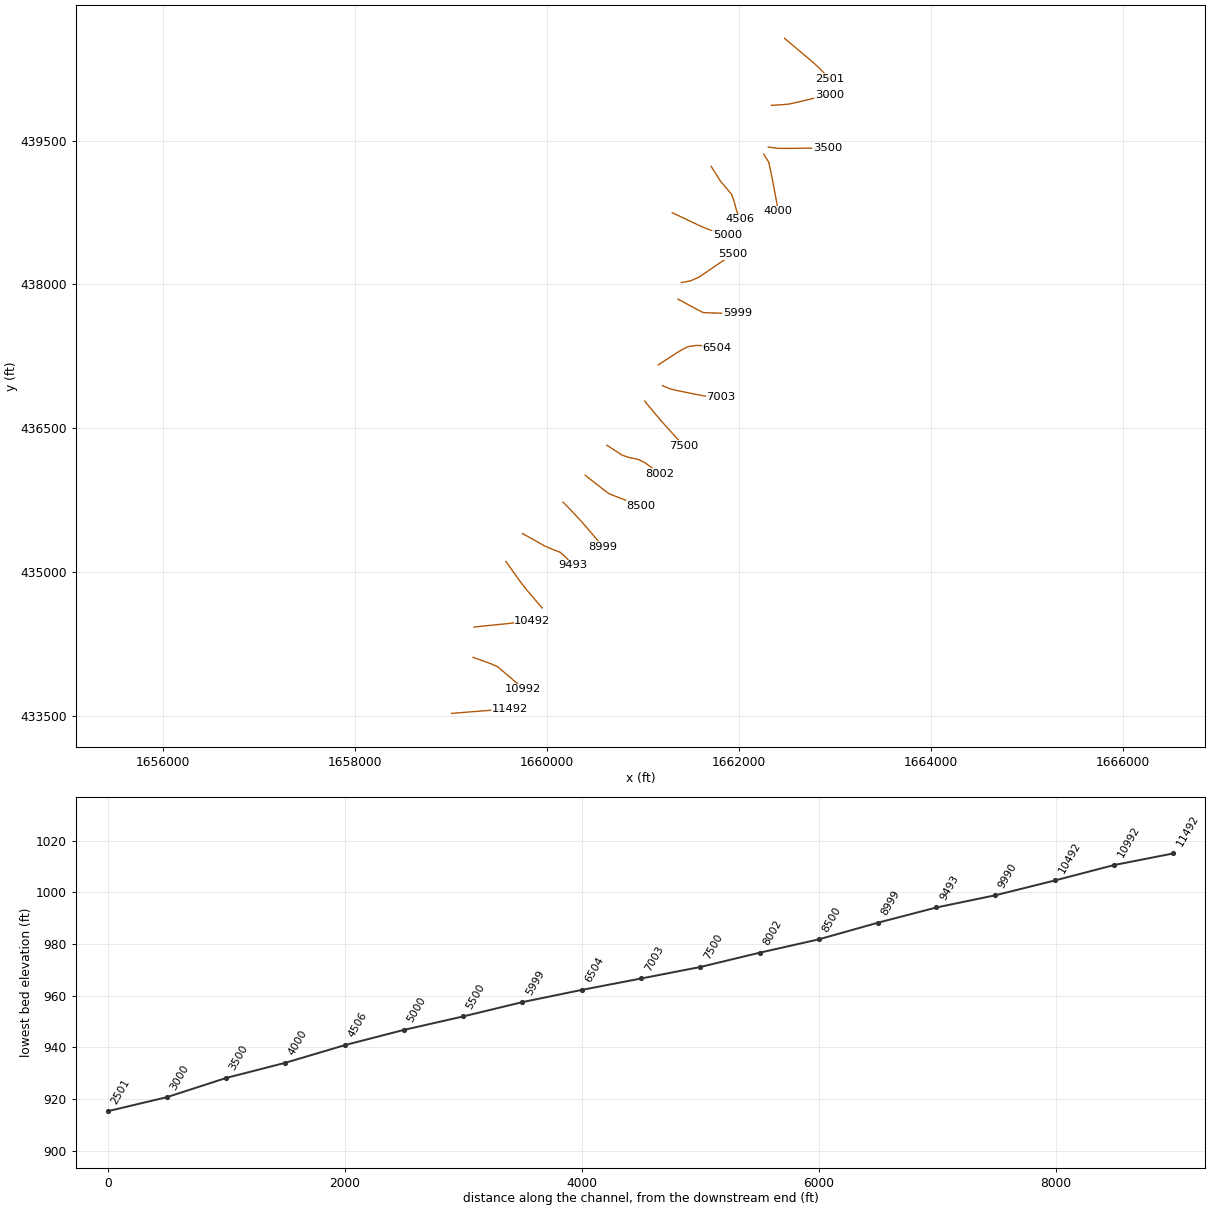
HEC-RAS study CARNEYFK.prj: CARNEYFK

--- CARNEYFK.g01 (geometry) --- (continued)

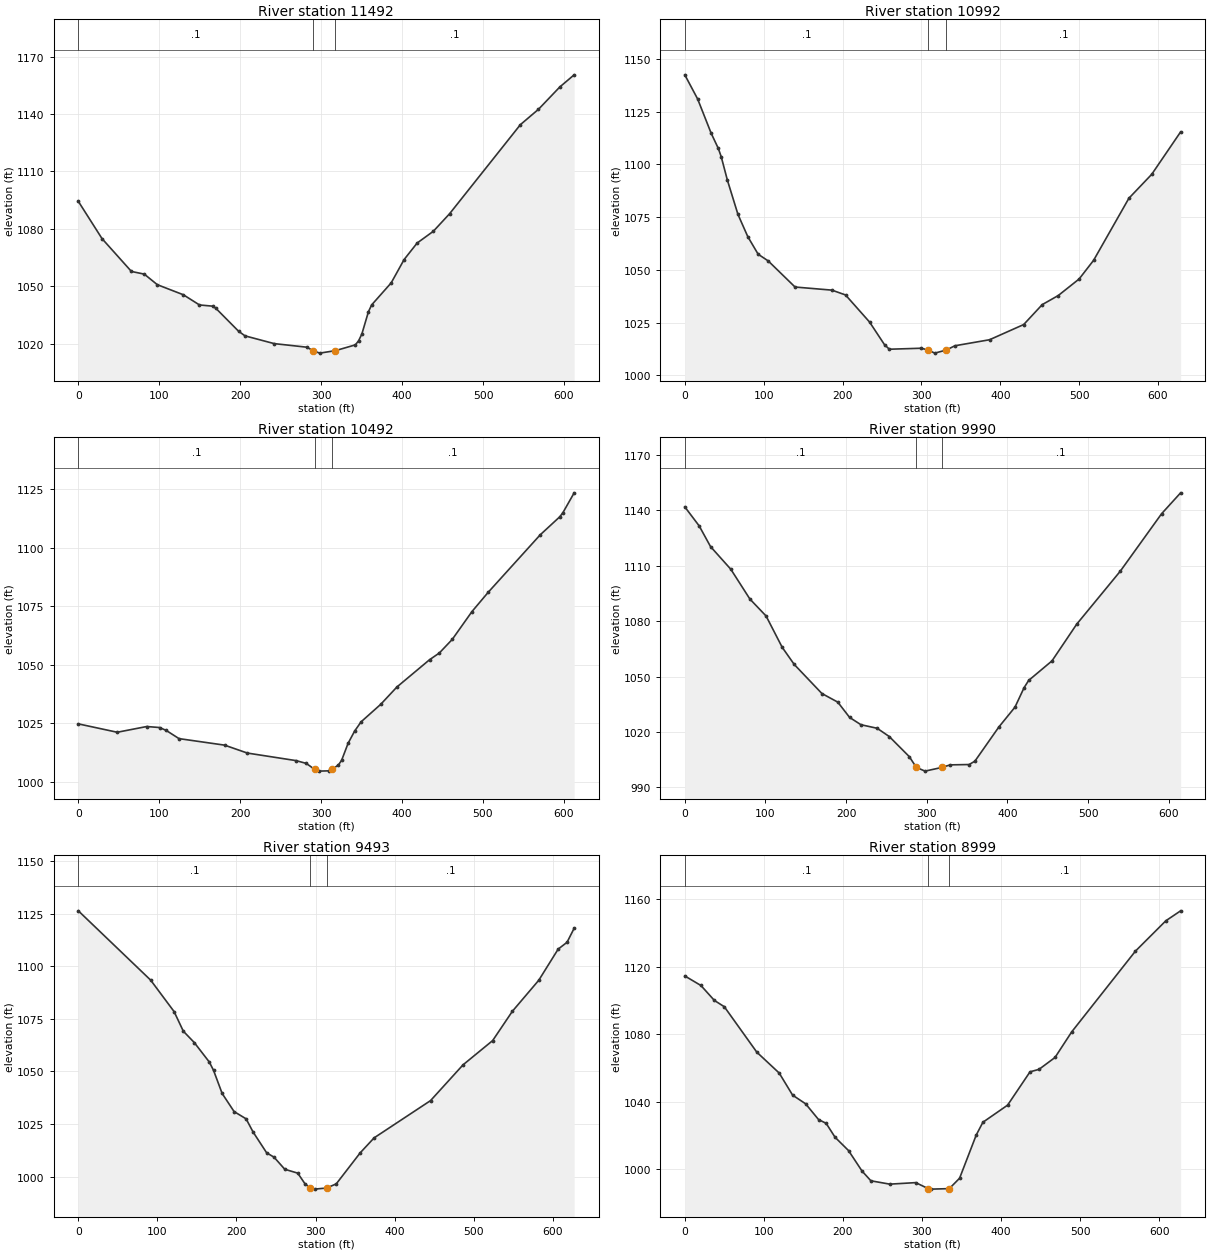
Type RM Length L Ch R = 1 ,11492   ,511.7,500,491.3
XS GIS Cut Line= 6
1659002.86198026433527.2310125081659096.32111092433534.609606668
1659258.31717801433547.3976388421659358.00693926433555.267701834
1659520.00300634433568.0547497571659613.74035168433571.909400836
#Sta/Elev= 30
       0 1094.32    29.3 1074.83    65.6 1057.69    81.5 1056.29    97.6 1050.77
   129.7 1045.52   149.7 1040.18   165.8 1039.56   169.8 1038.48   197.9 1026.49
   205.9 1024.04     242 1019.98   282.1 1018.12   290.2 1016.29   298.2 1015.01
   317.61016.298   342.3 1019.33   346.3 1021.48   350.3 1024.99   358.4 1036.61
   362.4 1040.21   386.5  1051.7   402.5 1063.91   418.6 1072.54   438.6 1078.68
   458.7 1087.85   546.2 1134.41   568.5 1142.42   594.9 1154.11   612.6 1160.44
#Mann= 3 ,-1,0
       0      .1       0   290.2    .045       0   317.6      .1       0
Bank Sta=290.2,317.6
XS Rating Curve= 0 ,0
Exp/Cntr(USF)=0,0
Exp/Cntr=0.3,0.1

Type RM Length L Ch R = 1 ,10992   ,487,500,506.4
XS GIS Cut Line= 6
1659228.75555734434111.6474945841659410.58130917434045.822823092
1659483.04310651 434014.417046011659616.38109443433901.076721504
1659682.43181534433843.6910095071659751.38935459433779.973289177
#Sta/Elev= 30
       0 1142.39    16.3 1130.93    33.4 1114.73    42.5 1107.51    46.2 1103.56
      54 1092.49    67.4 1076.26    79.9 1065.69      93 1057.39   105.8  1054.2
   139.8 1041.84   186.5 1040.37   203.8 1038.09   234.3 1025.24   253.3 1014.48
   259.4 1012.37     300 1012.84   308.5 1011.99     317 1010.52   331.5 1011.98
   342.5 1014.01   386.4 1016.86   429.7 1024.06   453.2  1033.5   473.5  1037.8
     500 1045.65   518.4 1054.52   563.1  1083.9   592.1 1095.27   628.7 1115.35
#Mann= 3 ,-1,0
       0      .1       0   308.5    .045       0   331.5      .1       0
Bank Sta=308.5,331.5
XS Rating Curve= 0 ,0
Exp/Cntr(USF)=0,0
Exp/Cntr=0.3,0.1

Type RM Length L Ch R = 1 ,10492   ,517.5,501.9,492.3
XS GIS Cut Line= 6
1659236.35003035434426.920814171 1659329.5316025 434437.27873309
1659590.71972843434463.4902948441659665.17561626434472.673675418
1659751.98777859434483.9151227621659846.03319417434489.518129915
#Sta/Elev= 30
       0 1024.73    48.1 1021.15    84.6  1023.6   100.4 1023.17   108.4 1021.98
   124.5 1018.43   180.8 1015.65   208.9 1012.27   269.2 1009.04   281.8 1007.85
  292.07 1005.32   297.4 1004.55   309.4 1004.67   313.4 1005.25   321.5 1007.16
   325.5 1009.16   333.5 1016.42   341.6 1021.66   349.6 1025.61   373.8 1033.06
   393.9 1040.49   434.2 1052.12   446.3 1054.99   462.3 1060.81   486.7 1072.71
   506.8 1080.95     571 1105.45   595.2 1113.16   599.1 1114.93     613  1123.4
#Mann= 3 ,-1,0
       0      .1       0  292.07    .045       0   313.4      .1       0
Bank Sta=292.07,313.4
XS Rating Curve= 0 ,0
Exp/Cntr(USF)=0,0
Exp/Cntr=0.3,0.1

Type RM Length L Ch R = 1 ,9990    ,487.4,497,502.2
XS GIS Cut Line= 6
1659570.13020268435111.1002200841659718.63515501434902.269601002
1659779.81154184434823.0666754251659829.03978984434765.640281096
1659886.22110592434698.2509801691659947.84106143434626.662540674
#Sta/Elev= 30
       0  1141.9    17.9 1131.55    31.9  1120.4    57.1  1108.1    80.7 1092.01
   100.8 1082.81   120.8 1065.84   135.7 1056.59     170 1040.85   189.7 1036.18
   204.4 1027.89   218.4 1023.96   238.5 1022.03   253.5 1017.57   278.3 1006.71
   287.1 1000.85   297.9  998.83   318.4  1000.8   329.2 1002.22   352.6  1002.4
   359.7 1004.22   389.5 1022.77   409.4 1033.46   420.7 1044.01   426.4 1047.95
   455.3 1058.51     486 1078.42   539.9 1107.03   591.2 1138.18   614.8  1149.5
#Mann= 3 ,-1,0
       0      .1       0   287.1    .045       0   318.4      .1       0
Bank Sta=287.1,318.4
XS Rating Curve= 0 ,0
Exp/Cntr(USF)=0,0
Exp/Cntr=0.3,0.1

Type RM Length L Ch R = 1 ,9493    ,493.8,493.8,487.2
XS GIS Cut Line= 6
1659744.50157309435401.964467749  1659972.666143435273.821679428
1660065.86805634435233.7728750111660135.81115793435206.699766427
  1660203.224737 435147.046998591660264.68885292435069.446103916
#Sta/Elev= 30
       0 1126.28    91.5 1093.36   121.1 1078.43   132.8 1069.11   146.6 1063.74
   165.6  1054.5     171 1050.53   181.9 1039.53     197 1030.94   212.2 1027.49
     221 1021.25   238.2 1011.34   247.5 1009.29   261.1 1003.54   277.5  1001.7
   286.6  996.68  293.32994.6518   298.8  994.11     314  994.64   326.2   996.6
   356.6 1011.39   374.1 1018.46   445.5 1036.16   486.6 1053.15     524 1064.65
   548.9 1078.54   582.4 1093.34   606.9 1108.11   618.1 1111.34   627.1 1118.01
#Mann= 3 ,-1,0
       0      .1       0  293.32    .045       0     314      .1       0
Bank Sta=293.32,314
XS Rating Curve= 0 ,0
Exp/Cntr(USF)=0,0
Exp/Cntr=0.3,0.1

Type RM Length L Ch R = 1 ,8999    ,484.2,499.1,500.4
XS GIS Cut Line= 6
1660164.92166401435730.170504257 1660234.2564991435660.076156259
1660345.28121142435541.534070507 1660412.0238601435465.631991342
1660462.41385117435405.7859824151660584.25087784435264.142564923
#Sta/Elev= 30
       0 1114.42    20.4 1108.76    37.4 1099.93      50 1096.18    91.1 1069.29
   119.4 1056.94   136.4 1043.85   152.8 1038.74   169.2  1029.4   178.8 1027.17
   190.1 1018.91   207.1 1011.05   224.2  998.92   235.4  993.15   259.3  991.17
   292.1  992.07   307.7  988.57   311.9  988.22   334.6  988.52   347.6  994.68
   368.7 1020.29   377.1 1027.81   408.3 1037.92   436.7 1057.66   448.1 1059.13
   468.3 1066.15   489.4 1081.29     570 1129.09   608.5 1147.07   627.2 1152.96
#Mann= 3 ,-1,0
       0      .1       0   307.7    .045       0   334.6      .1       0
Bank Sta=307.7,334.6
XS Rating Curve= 0 ,0
Exp/Cntr(USF)=0,0
Exp/Cntr=0.3,0.1

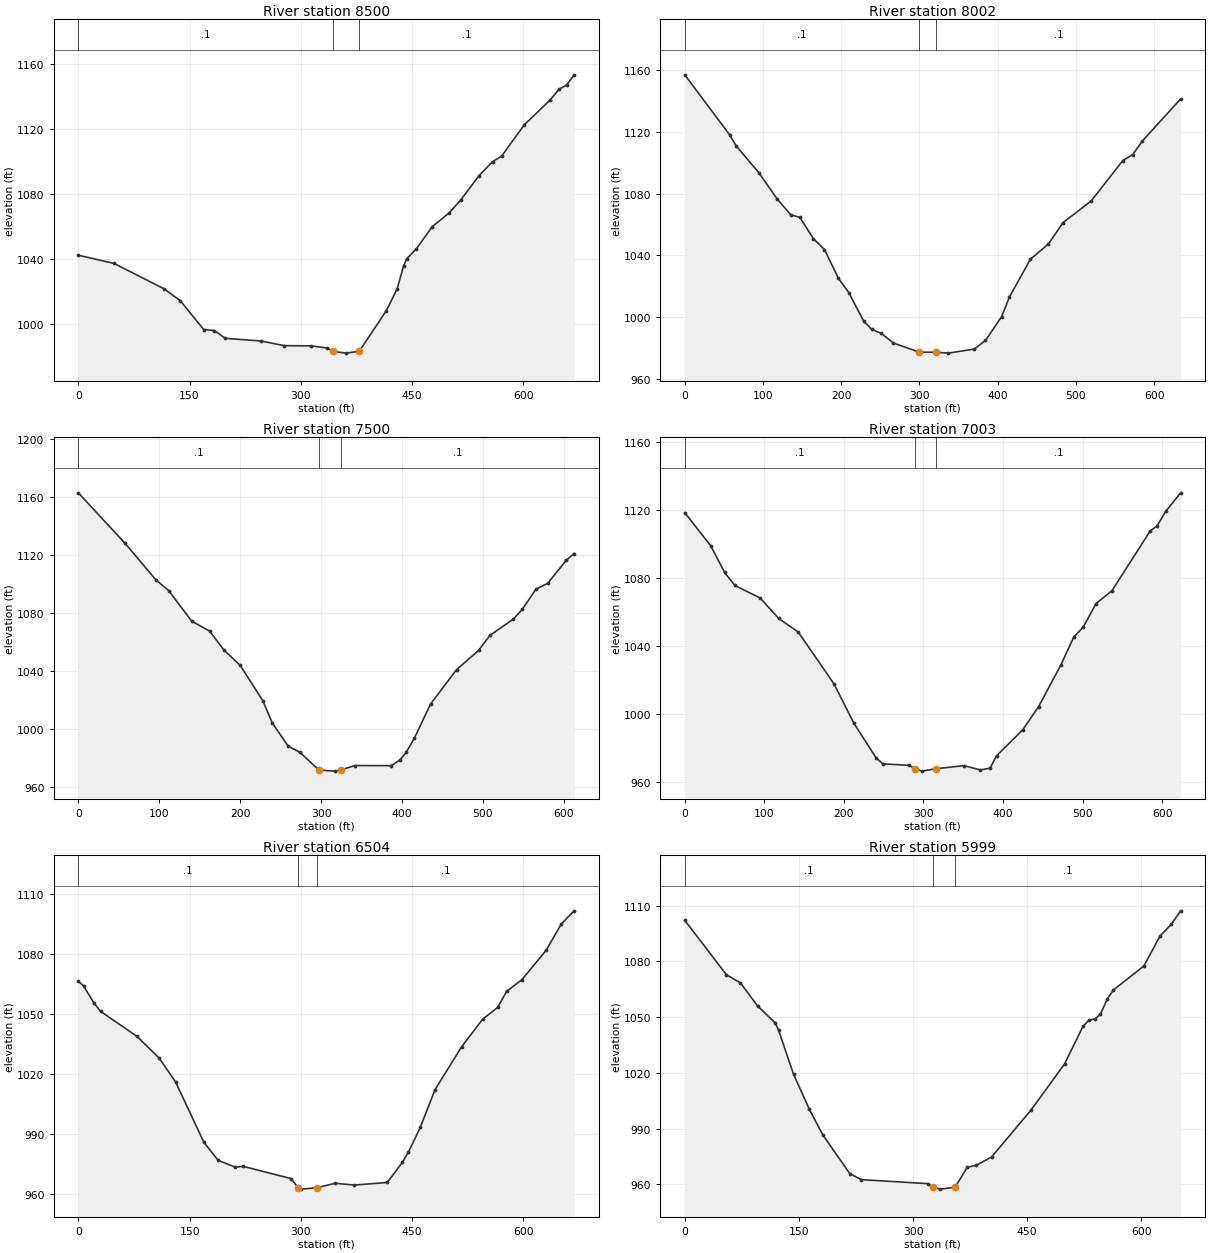
Type RM Length L Ch R = 1 ,8500    ,494.4,498.2,495.2
XS GIS Cut Line= 6
1660396.39561051436010.3287365881660564.05898909435878.357543841
1660642.65922558435818.2746587541660805.50798126435754.201296091
1660887.04882868435722.4615301791660974.57457225435688.862187922
#Sta/Elev= 30
       0  1042.1    48.1 1037.06     115 1021.56   137.2 1014.19   169.1  996.32
   183.4  995.72   198.2   990.9   246.1  989.28   277.5  986.38   313.9  986.25
   335.4  984.95     344  982.82   361.2  981.78  378.85982.9484   415.4 1007.99
   429.9 1021.35   438.5 1035.38   442.8 1039.88   455.7 1045.95   477.2 1059.69
   499.9  1068.1   515.9 1076.27     540 1090.97   558.6  1099.8   570.9 1103.21
   601.1 1122.33     636 1137.65   648.3 1144.43   658.3 1146.88   668.6 1153.25
#Mann= 3 ,-1,0
       0      .1       0     344    .045       0  378.85      .1       0
Bank Sta=344,378.85
XS Rating Curve= 0 ,0
Exp/Cntr(USF)=0,0
Exp/Cntr=0.3,0.1

Type RM Length L Ch R = 1 ,8002    ,508.6,502,494.4
XS GIS Cut Line= 6
1660623.10873976436323.395039588 1660779.5231251436220.624903917
1660850.65159176436195.9953600021660948.54575293436175.255900174
  1661018.345154436140.8356934191661175.21787176436027.640381753
#Sta/Elev= 30
       0 1156.97    57.3 1118.13    65.9 1110.75    94.7 1093.53   117.9 1076.63
   135.4 1066.28     147 1064.63   164.5 1050.76   178.6 1043.77   196.3 1025.21
   209.8 1015.72   228.7  997.32   238.7  992.17   251.4  989.39   266.7  983.17
  299.99977.2465   321.3   977.2   337.1  976.63   370.3  979.29   384.4  984.85
   404.9 1000.14   415.1 1013.03   441.9 1037.53   464.9 1047.35   483.4  1061.1
   519.6  1075.3   559.8 1101.29   572.7 1105.34   584.9 1114.04   633.9 1141.35
#Mann= 3 ,-1,0
       0      .1       0  299.99    .045       0   321.3      .1       0
Bank Sta=299.99,321.3
XS Rating Curve= 0 ,0
Exp/Cntr(USF)=0,0
Exp/Cntr=0.3,0.1

Type RM Length L Ch R = 1 ,7500    ,481.9,497.3,500.1
XS GIS Cut Line= 6
1661016.92192851436782.6349347531661132.41283926436642.705096513
1661180.75690268436585.3046207581661247.59010234436510.917958513
1661356.56757468436390.3768610061661418.51692584436320.000033259
#Sta/Elev= 30
       0 1163.18    57.8 1128.32      96 1102.97   111.7 1095.71   140.1  1074.6
   162.2 1067.75   179.9 1054.72     200 1044.11   228.2 1019.51   239.5 1004.52
   259.4  988.24   273.6   984.2  297.19  971.89   316.7  971.09   324.5  971.91
   341.5  974.93   386.7  974.87   397.4   978.8     405  983.96   415.2   993.8
   435.2 1017.37   467.5  1041.2   494.5 1054.36   508.6 1064.79   537.4 1075.96
   548.6 1082.77   565.3 1096.53   580.1 1100.77     603 1116.67   612.7  1121.3
#Mann= 3 ,-1,0
       0      .1       0  297.19    .045       0   324.5      .1       0
Bank Sta=297.19,324.5
XS Rating Curve= 0 ,0
Exp/Cntr(USF)=0,0
Exp/Cntr=0.3,0.1

Type RM Length L Ch R = 1 ,7003    ,487.7,498.4,505.3
XS GIS Cut Line= 6
1661201.71486601436944.3957660941661289.44959867436908.512963846
1661374.90316792436889.209196672  1661622.623473436839.042302251
  1661713.505181436831.6082620021661810.31141783436828.009187832
#Sta/Elev= 30
       0  1118.7    32.8 1099.01    50.1 1083.48      63 1075.85    94.8 1068.46
     118 1056.45   142.6 1048.46   187.7 1017.86   212.2  995.08   240.8  974.22
     249  970.95   282.1  970.07   289.8  968.02     298  966.66     316  968.11
   351.1  969.87   371.5  967.35   383.7  968.41   391.8  975.69   424.9  991.04
   444.7 1004.61   472.8 1029.23   488.8 1045.41   500.9 1051.47   516.9 1065.21
     537 1072.84     585 1107.94   593.6 1110.93   604.8 1119.61   623.2 1130.33
#Mann= 3 ,-1,0
       0      .1       0   289.8    .045       0     316      .1       0
Bank Sta=289.8,316
XS Rating Curve= 0 ,0
Exp/Cntr(USF)=0,0
Exp/Cntr=0.3,0.1

Type RM Length L Ch R = 1 ,6504    ,503.1,505.5,491.7
XS GIS Cut Line= 6
1661158.12735476437161.1518942561661372.97535026  437300.8100795
1661464.66808026437350.2007287591661553.49861126437363.730885416
1661658.51480542437359.8821398321661768.91550326437335.703382418
#Sta/Elev= 30
       0 1066.22     7.1 1063.96    20.9 1055.41    29.9 1051.23    78.7 1038.79
     109 1027.83   131.2 1015.84   169.3  985.66   188.4  976.72   211.7  973.21
   221.8   973.7   287.1  967.52   296.2  962.96   300.7  962.27  321.63962.9672
   346.1   965.2     372   964.3   416.5  965.61   436.7   975.6   444.8  980.65
   460.9  993.14   480.9 1012.07   516.9  1033.6   544.9 1047.21   565.2 1053.14
   577.5 1061.29   597.9 1067.03   630.7 1081.81   651.2 1094.98   668.4  1101.5
#Mann= 3 ,-1,0
       0      .1       0   296.2    .045       0  321.63      .1       0
Bank Sta=296.2,321.63
XS Rating Curve= 0 ,0
Exp/Cntr(USF)=0,0
Exp/Cntr=0.3,0.1

Type RM Length L Ch R = 1 ,5999    ,487.5,498.7,505.3
XS GIS Cut Line= 6
1661364.06821585437846.5990141781661456.69073401437795.807121009
1661547.05636692437747.0522972491661624.29144867437706.623572335
1661724.22628817437702.1239094291661980.43476526437697.509089261
#Sta/Elev= 30
       0 1102.15    54.8 1072.81      73 1068.56    95.9 1055.97   118.6 1047.06
   123.2 1043.13     143 1019.27   163.7  1000.5   181.4   986.7   216.9  965.85
   232.1  962.61   319.3  960.45   326.8958.5787   335.6   957.5   355.4  958.53
   371.4  969.32   383.4  970.32   403.4  974.85   455.4 1000.17   499.2 1024.87
   523.4 1045.08   531.4 1048.47   539.4  1049.1   546.3  1051.6   555.4 1059.78
   563.4 1064.66   603.4 1077.54   624.9 1093.77   639.5 1099.98   651.8 1107.26
#Mann= 3 ,-1,0
       0      .1       0   326.8    .045       0   355.4      .1       0
Bank Sta=326.8,355.4
XS Rating Curve= 0 ,0
Exp/Cntr(USF)=0,0
Exp/Cntr=0.3,0.1

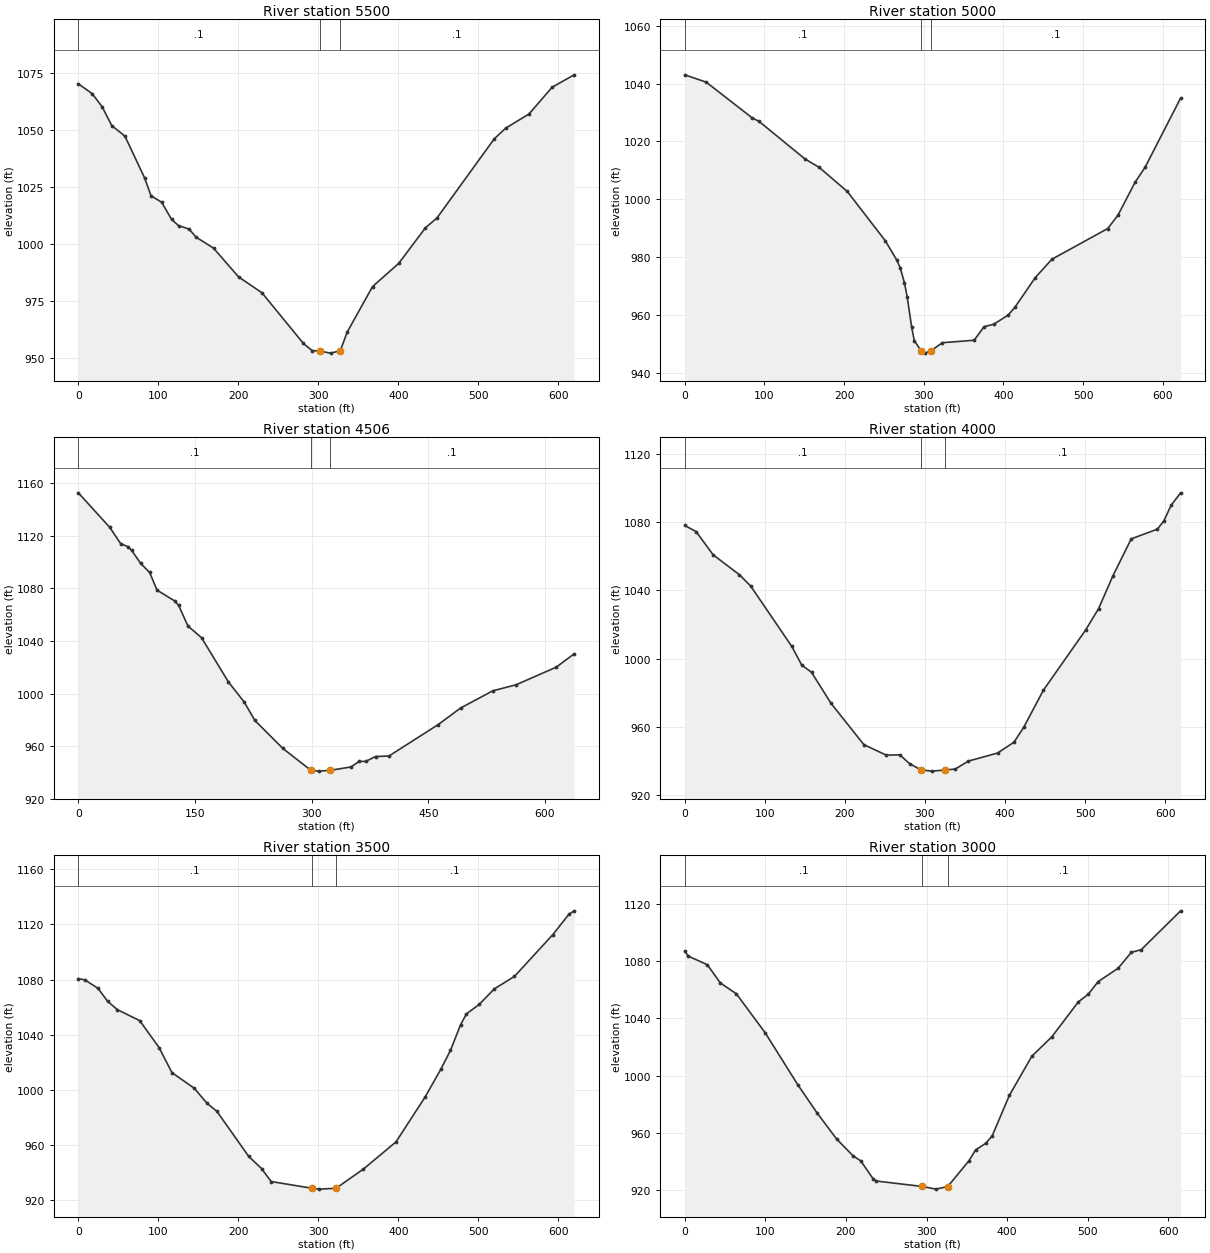
Type RM Length L Ch R = 1 ,5500    ,510,500.1,492.5
XS GIS Cut Line= 6
1661399.03304093438018.2541826671661496.38323992438037.937214166
1661577.93983534438073.9850423341661640.46136384438115.421639249
 1661723.0842301438171.7555160821661934.80395101438316.112182751
#Sta/Elev= 30
       0 1070.17    17.4  1065.8    29.7  1060.1    41.9 1051.78    58.2 1047.21
    82.7 1028.96    90.9 1021.02   104.1 1018.19   116.5 1010.68   125.3  1007.9
   138.4 1006.44   147.1 1002.88     169  998.04   200.3  985.42   229.5  978.46
   281.3  956.24   292.1  953.11   301.5   952.9   315.2  951.98   327.4     953
     336  961.18   367.7  981.17   400.4  991.35   433.9    1007   448.3 1011.31
   519.7 1045.96   534.2 1050.73   563.2 1056.89   592.2 1068.66   619.7  1074.1
#Mann= 3 ,-1,0
       0      .1       0   301.5    .045       0   327.4      .1       0
Bank Sta=301.5,327.4
XS Rating Curve= 0 ,0
Exp/Cntr(USF)=0,0
Exp/Cntr=0.3,0.1

Type RM Length L Ch R = 1 ,5000    ,496.4,493.9,489.8
XS GIS Cut Line= 6
1661303.83670901438747.7146660091661535.30146918438637.768691674
1661625.77799426438595.0722547621661697.45468818438567.597900257
 1661784.6290545438541.5940152561661878.77158275438512.636724085
#Sta/Elev= 30
       0 1043.07    26.9 1040.53    84.4 1028.22    93.3 1026.95   150.9 1013.95
   168.6 1011.07     204 1002.71   251.8  985.62     266  979.03   270.4  976.33
   275.8  971.05   279.3  966.11   284.8  955.78   288.1  951.11  296.67  947.57
   301.4  946.77   308.9  947.58   323.5  950.38   363.2  951.23   375.9  955.94
   387.9  956.77   405.9  959.93   414.5  962.65     440   972.9   460.9  979.26
   530.9  989.87   543.7  994.43   565.3 1005.88   577.9 1011.09   622.5 1035.02
#Mann= 3 ,-1,0
       0      .1       0  296.67    .045       0   308.9      .1       0
Bank Sta=296.67,308.9
XS Rating Curve= 0 ,0
Exp/Cntr(USF)=0,0
Exp/Cntr=0.3,0.1

Type RM Length L Ch R = 1 ,4506    ,504.3,505.8,490.9
XS GIS Cut Line= 6
1661708.68334025439231.1897489281661805.97284384439076.000426754
1661920.88534367438941.0620483461661948.64020942438864.665219501
1661972.14541176438774.504310593 1662009.8923835438679.036981836
#Sta/Elev= 30
       0 1152.84    40.4 1126.56    54.4 1114.19    63.7  1111.8    68.4 1109.14
    80.2 1099.07    91.7 1092.21   101.2 1078.74   123.7 1070.61   128.9 1067.25
     141  1051.4   158.4 1042.53     193 1008.86   213.3  993.55     227  979.54
     263  958.22   299.1  941.54   309.3  940.94   323.7  941.52   350.5  944.12
   361.1  948.31   369.6  948.37   382.3  952.07   399.4  952.43   462.6  976.32
   491.5  988.96   532.9 1002.07   562.9 1006.69   614.5 1020.07   637.6 1030.25
#Mann= 3 ,-1,0
       0      .1       0   299.1    .045       0   323.7      .1       0
Bank Sta=299.1,323.7
XS Rating Curve= 0 ,0
Exp/Cntr(USF)=0,0
Exp/Cntr=0.3,0.1

Type RM Length L Ch R = 1 ,4000    ,471.1,500.1,514.4
XS GIS Cut Line= 6
1662256.71144368439358.7547825131662309.19591875439272.932775676
1662327.54168259439187.3512539271662342.93633685 439113.93374984
1662361.72435701439015.7141299991662409.36041659438763.930840924
#Sta/Elev= 30
       0 1078.12    14.2  1074.5    35.4 1060.91    68.2 1049.25    82.3  1042.6
   133.7 1007.16     146  996.33   158.3  992.01   182.8  973.74   223.7  949.59
   251.8  943.42   268.6  943.63   280.9   938.4  295.24934.7507   309.4  934.06
   325.6  934.74   337.9  935.29   354.2  939.94   390.8  944.67   411.2  951.03
   423.4  959.74   447.8   981.4   500.7 1016.81     517 1029.41   534.8 1048.58
   557.7 1070.26   590.3 1075.95   598.4 1080.77   607.5 1089.93   619.4 1097.26
#Mann= 3 ,-1,0
       0      .1       0  295.24    .045       0   325.6      .1       0
Bank Sta=295.24,325.6
XS Rating Curve= 0 ,0
Exp/Cntr(USF)=0,0
Exp/Cntr=0.3,0.1

Type RM Length L Ch R = 1 ,3500    ,496.8,500,504.2
XS GIS Cut Line= 6
1662303.91476133439431.6857390111662403.60189793439418.794032499
 1662491.5016565439417.8668690031662566.49625717439418.750069335
1662741.48442426439420.8081360911662922.69928493439423.208065674
#Sta/Elev= 30
       0  1080.8     8.3 1079.79    24.4 1073.81    36.5 1064.42    48.6 1058.31
    76.8 1050.28     101  1030.7     117 1012.61     145 1001.28     161  990.25
     173  984.71     213  951.86     229  943.07     241  933.69  291.49928.8568
     301  928.18   322.1  928.79   356.4  942.77     397   962.4   433.1  994.67
   453.1 1015.11   465.1 1028.75   477.8 1047.42   485.1 1055.22   501.1 1062.09
   519.7 1073.23   545.1 1082.38   593.1  1112.7   613.1 1127.38   619.7  1129.9
#Mann= 3 ,-1,0
       0      .1       0  291.49    .045       0   322.1      .1       0
Bank Sta=291.49,322.1
XS Rating Curve= 0 ,0
Exp/Cntr(USF)=0,0
Exp/Cntr=0.3,0.1

Type RM Length L Ch R = 1 ,3000    ,510.5,498.9,483.6
XS GIS Cut Line= 6
1662336.11023501439867.5267308351662431.56706509 439872.43977876
1662519.80999884439880.2809704241662593.15827735439896.027001917
1662690.42711167439919.2385696771662939.67858167439978.717453346
#Sta/Elev= 30
       0  1086.9       4 1083.39      28 1077.28    44.1 1064.61    64.1 1056.97
    99.9 1029.72   140.3  993.52   164.4  973.75   188.6  955.62     209  943.92
   218.3  940.51   233.6  928.08   237.7  926.41   294.9   922.6   311.6  920.76
  326.34922.5751   352.7  940.56   360.9  948.09   373.3  952.62   381.5  957.88
   402.9  986.23   430.8 1013.52   455.5 1026.97   488.4 1051.37   500.7 1056.65
   513.1 1065.57   537.8 1074.81   554.2 1085.94   566.5  1087.8   615.4  1114.9
#Mann= 3 ,-1,0
       0      .1       0   294.9    .045       0  326.34      .1       0
Bank Sta=294.9,326.34
XS Rating Curve= 0 ,0
Exp/Cntr(USF)=0,0
Exp/Cntr=0.3,0.1

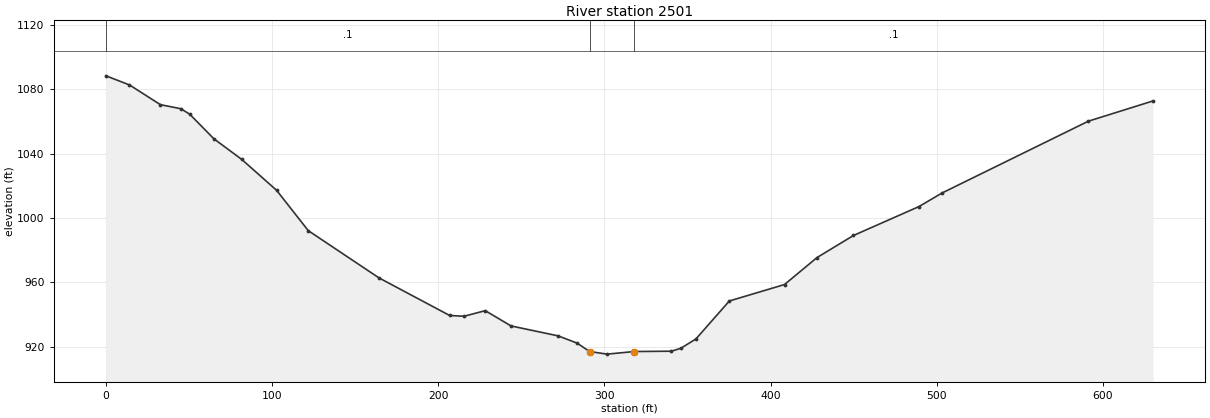
Type RM Length L Ch R = 1 ,2501    ,504.4,501.1,495.4
XS GIS Cut Line= 6
1662473.62111484440565.6608332541662669.48981759440400.473171502
1662746.02214484440335.6117526741662806.48691893440283.484232262
1662872.93363643440217.8341010961662943.41413851440146.255176008
#Sta/Elev= 30
       0 1088.33    14.2 1082.67    32.8  1070.4    45.1 1067.88    50.4 1064.52
      65 1049.18    81.8 1036.33   102.7  1017.2   121.8  992.08   164.4  962.69
   206.9  939.35   215.5  938.87   228.3  942.35   243.8  932.86   272.2  926.67
   283.6  922.17   291.1  916.95   301.6  915.33     318  916.94   340.3  917.15
     346  918.95   355.1  924.77   375.2  948.37   408.4  958.59     428  975.39
   449.9  989.08   489.3 1007.05   503.2 1015.49   591.3 1060.15   630.2 1072.73
#Mann= 3 ,-1,0
       0      .1       0   291.1    .045       0     318      .1       0
Bank Sta=291.1,318
XS Rating Curve= 0 ,0
Exp/Cntr(USF)=0,0
Exp/Cntr=0.3,0.1