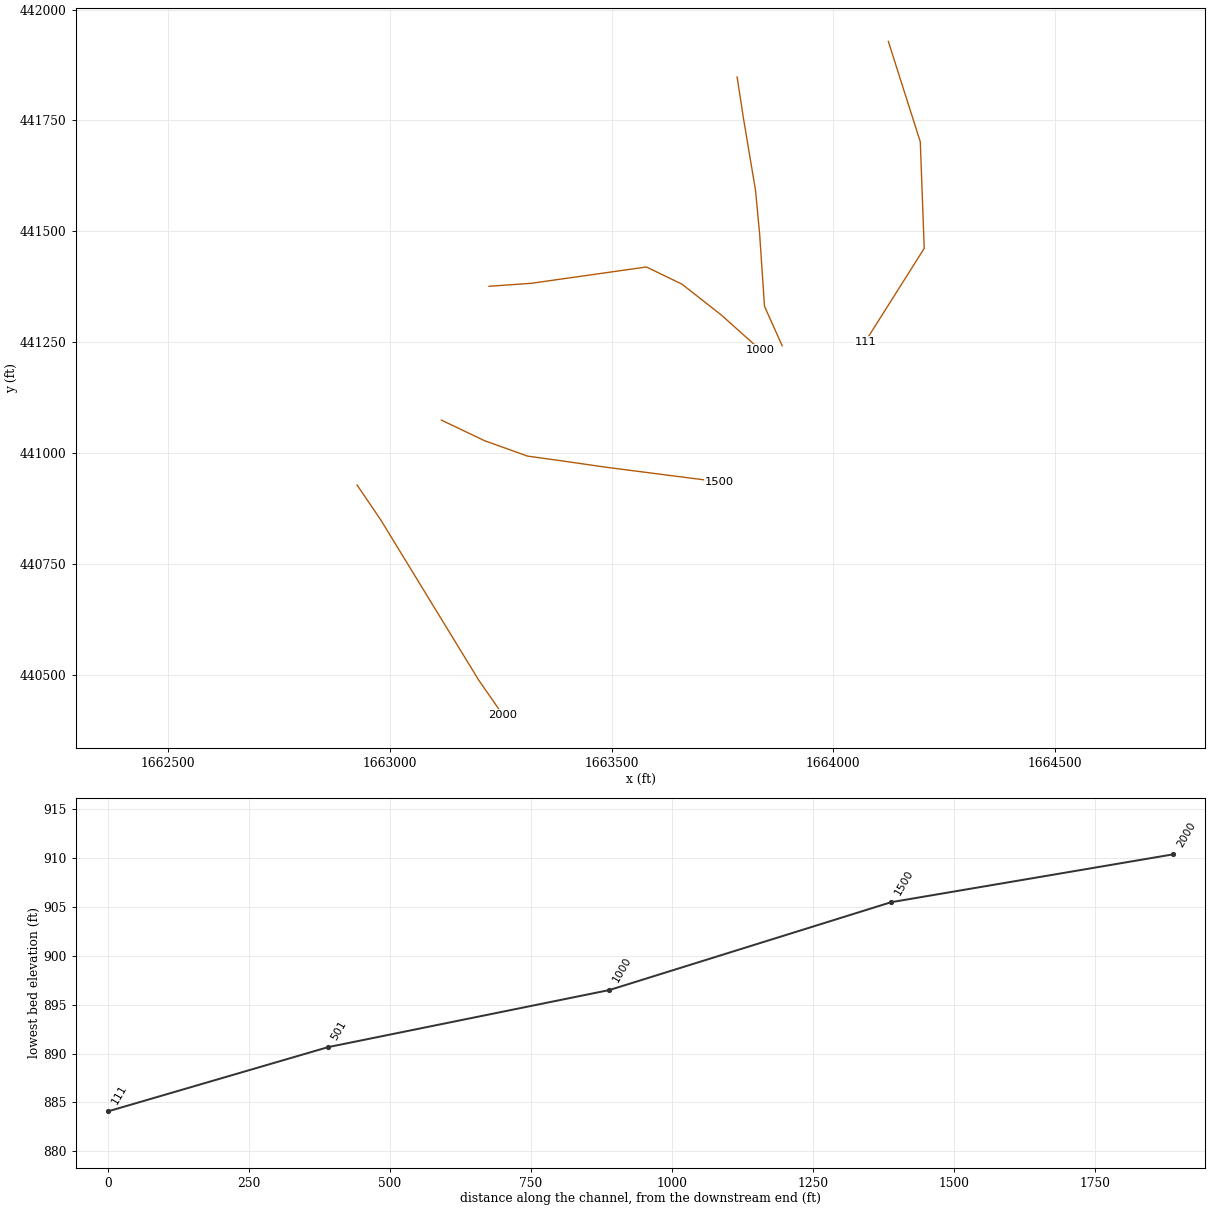
HEC-RAS study CARNEYFK.prj: CARNEYFK

--- CARNEYFK.g01 (geometry) --- (continued)

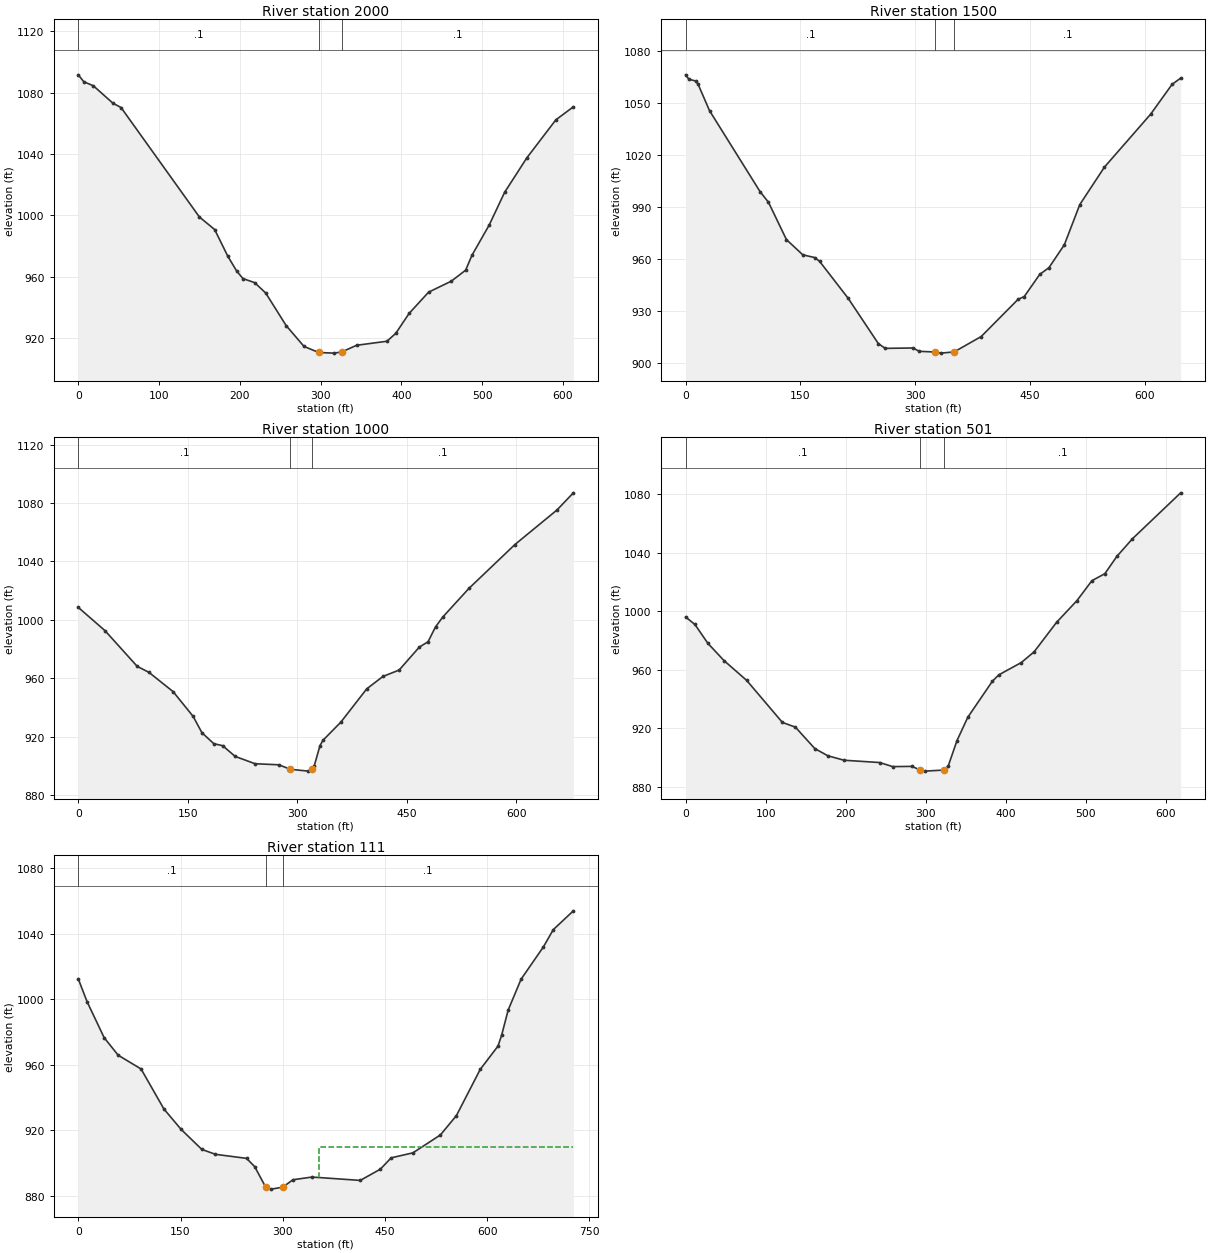
Type RM Length L Ch R = 1 ,2000    ,487,500.5,508.7
XS GIS Cut Line= 6
1662926.08444875440927.987536415 1662978.8432015440850.361707419
1663024.50485559440775.7207805961663063.64421301440711.743218258
1663200.62851909440487.8201096651663254.26489475440410.698872834
#Sta/Elev= 30
       0 1091.62     6.8 1087.13    18.7 1084.46    42.9 1073.12    52.9 1070.33
   149.9  999.03   168.8  990.84   185.1  973.44   195.9  963.93   203.8   958.9
   218.3  956.26     232  949.49   257.3  928.27   279.4   914.7   297.6  910.75
   316.4  910.34   325.9  911.07   344.5  915.45     382  918.08   392.9  923.17
   409.5  936.22   433.6  950.06   461.7  957.21   479.5  964.38   487.2  974.01
   508.6  993.77   527.7 1015.08   555.3 1037.61   591.1 1062.29   612.8 1070.79
#Mann= 3 ,-1,0
       0      .1       0   297.6    .045       0   325.9      .1       0
Bank Sta=297.6,325.9
XS Rating Curve= 0 ,0
Exp/Cntr(USF)=0,0
Exp/Cntr=0.3,0.1

Type RM Length L Ch R = 1 ,1500    ,487.7,499.5,499.3
XS GIS Cut Line= 6
1663116.26123376441074.4127685131663214.00939783441027.833137259
1663310.59975584440993.2610279171663389.62584451440982.348648176
1663488.60235259440968.0491360871663742.85053176440935.442574009
#Sta/Elev= 30
       0 1066.09     4.3 1063.54    13.1 1062.54    16.3  1060.7    31.3 1045.38
    97.3  998.69   108.3  992.55   131.8  970.98   153.2  962.19   168.8  960.61
   175.1  958.45   212.4  937.14   251.9  910.96   260.9   908.2   297.2  908.42
   305.3   906.5   326.2  906.08   333.3  905.45   350.9  906.14   386.3  915.02
   434.5  936.49   442.6  938.12   462.8  950.88   474.9  954.79     495  968.01
   515.2  991.21   547.4 1012.83   607.8 1043.39   635.8  1060.6     647 1064.18
#Mann= 3 ,-1,0
       0      .1       0   326.2    .045       0   350.9      .1       0
Bank Sta=326.2,350.9
XS Rating Curve= 0 ,0
Exp/Cntr(USF)=0,0
Exp/Cntr=0.3,0.1

Type RM Length L Ch R = 1 ,1000    ,522.7,498.7,475.5
XS GIS Cut Line= 6
1663223.64487725441376.1844746771663318.63746943441382.868188336
1663578.54016484441419.704072669 1663658.9205815441380.843914166
1663747.06673068 441311.766624511663835.80277367 441232.51514259
#Sta/Elev= 30
       0 1008.52    36.6   992.6    80.7  968.17    96.7  964.09   129.9  950.87
   157.3  933.92   169.4   922.7   185.6  915.26   197.7  913.89   214.8  906.56
   242.2  901.53   274.5  900.82   290.6  897.72   314.9  896.48  320.01897.8103
     323  899.84     331  913.95   335.1   917.6   359.5  929.96     395  952.77
   417.2  961.27   439.4  965.65     467  981.34     479  985.01   489.2  995.18
   499.3 1002.02   534.9 1021.49   597.9 1051.52   655.5 1075.16     678 1086.93
#Mann= 3 ,-1,0
       0      .1       0   290.6    .045       0  320.01      .1       0
Bank Sta=290.6,320.01
XS Rating Curve= 0 ,0
Exp/Cntr(USF)=0,0
Exp/Cntr=0.3,0.1

Type RM Length L Ch R = 1 ,501     ,388.7,390.3,388.5
XS GIS Cut Line= 6
1663783.15852201441847.9748696681663797.54891318441754.149598002
1663824.64367525441592.7230835861663833.99798726 441493.12748225
 1663844.9517055441330.9969010061663884.74526109441242.130280837
#Sta/Elev= 30
       0  996.03    11.6  990.97    27.8  978.06      48  966.22    76.3   952.7
   120.9  923.96   137.2  920.71   161.5  906.03   177.8  901.13     198   898.1
   242.6  896.52   258.8  893.73   282.9   893.9  292.85891.4296     299  890.65
   323.1   891.4   328.1  894.16   339.1  911.56   352.5  927.41   383.3  952.13
   391.3  956.46   419.4  964.88   435.4  972.19   463.5   992.4   488.9 1007.19
   507.6 1020.83   523.8 1025.64   538.7 1037.39   558.2 1049.48   618.5 1080.91
#Mann= 3 ,-1,0
       0      .1       0  292.85    .045       0   323.1      .1       0
Bank Sta=292.85,323.1
XS Rating Curve= 0 ,0
Exp/Cntr(USF)=0,0
Exp/Cntr=0.3,0.1

Type RM Length L Ch R = 1 ,111     ,,,
XS GIS Cut Line= 4
  1664124.205237441928.2628235191664196.29027053441701.890525217
1664205.14281851441461.6070800921664072.35459884441251.675228035
#Sta/Elev= 30
       0 1012.34    12.9  998.43    37.9  976.53    58.5  965.81    92.1   957.4
   125.6     933   150.8  920.57   181.2  908.34   201.2  905.33   246.9  902.86
   258.9  897.77     275  885.24     283  884.09  299.68885.2458     315  889.81
   342.9  891.46   413.7  889.41   443.1  896.24   459.1  903.18     491  906.23
   531.3  917.15   554.8  928.95   589.7  957.12   615.8  971.35   621.3  978.22
   630.7  993.29   649.7 1012.19   682.5 1031.93   696.9 1042.39   726.4 1053.89
#Mann= 3 ,-1,0
       0      .1       0     275    .045       0  299.68      .1       0
#XS Ineff= 2 , 0
                           353.8             910
Permanent Ineff=
       F       F
Bank Sta=275,299.68
XS Rating Curve= 0 ,0
Exp/Cntr(USF)=0,0
Exp/Cntr=0.3,0.1
LCMann Table=0

Chan Stop Cuts=-1
Use User Specified Reach Order=0
Composite Channel Slope=5